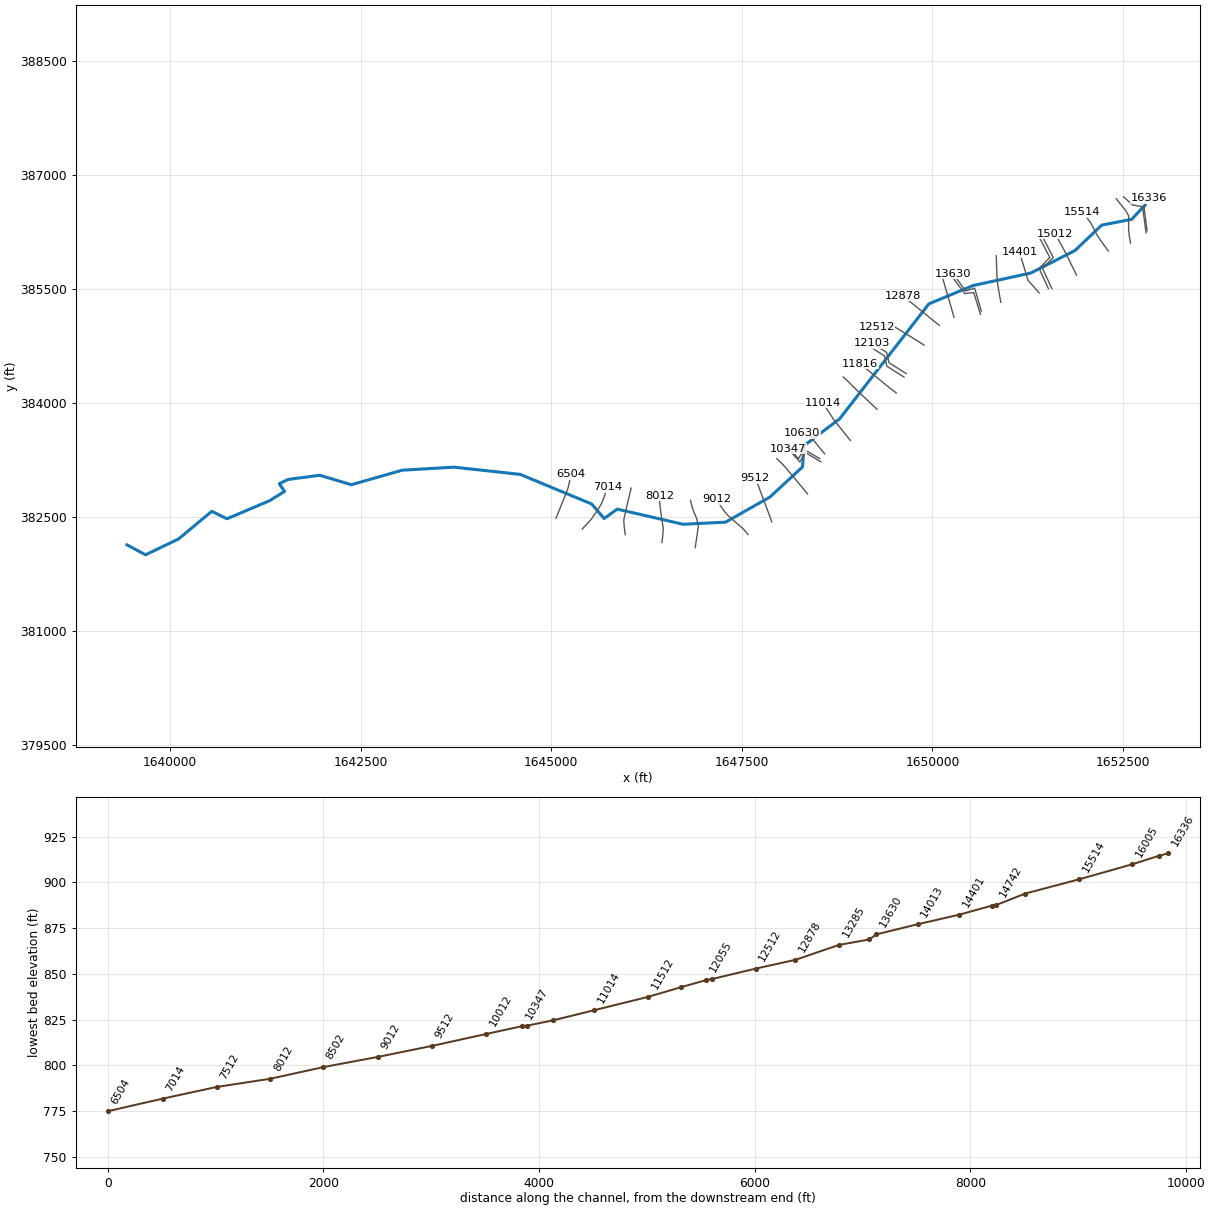
--- UPPERRN.prj (project) ---

Proj Title=UPPERRN
Current Plan=p01
Default Exp/Contr=0,0
English Units
Geom File=g01
Flow File=f01
Plan File=p01
BEGIN DESCRIPTION:
---------- MODELED AS PART OF WVEMD CTP PROGRAM, 2023----------
Stream Name: Upper Run
Flood Zone:  AFH
Wetzel County, WV
HEC-RAS Version: RAS 6.3
Vertical Datum: NAVD88
Projection: NAD 1983 StatePlane West Virginia S FIPS 4702 (US Feet)
Terrain: 1-meter West Virginia FEMA R3 South Central (collected 2018-2020)
Land Use: 2019 NLCD
Hydrologic Method:
WV 2010 Regional Regression Equations
Additional Model Notes:
None
END DESCRIPTION:
DSS Export Rating Curves= 0
DSS Export Rating Curve Sorted= 0
DSS Export Volume Flow Curves= 0
DXF OffsetX= 0
DXF OffsetY= 0
DXF ScaleX= 0
DXF ScaleY= 0

--- UPPERRN.p01 (plan) ---

Plan Title=Floodplain
Program Version=6.30
Short Identifier=Floodplain
Geom File=g01
Flow File=f01
Subcritical Flow
K Sum by GR= 0
Std Step Tol= 0.01
Critical Tol= 0.01
Num of Std Step Trials= 20
Max Error Tol= 0.3
Flow Tol Ratio= 0.001
Split Flow NTrial= 30
Split Flow Tol= 0.02
Split Flow Ratio= 0.02
Log Output Level= 0
Friction Slope Method= 1
Unsteady Friction Slope Method= 2
Unsteady Bridges Friction Slope Method= 1
Parabolic Critical Depth
Global Vel Dist= 0 , 0 , 0
Global Log Level= 0
CheckData=False
Encroach Param=-1 ,0,0, 0
Mapping Interval=1HOUR
Computation Time Step Use Courant=        0
Computation Time Step Use Time Series=    0
Computation Time Step Count To Double=0
Computation Time Step Max Doubling=0
Computation Time Step Max Halving=0
Computation Time Step Residence Courant=0
Run HTab= 0
Run UNet= 0
Run Sediment= 0
Run PostProcess= 0
Run WQNet= 0
Run RASMapper=-1
UNET Theta= 0
UNET Theta Warmup= 0
UNET ZTol= 0
UNET ZSATol= 0
UNET MxIter= 0
UNET Max Iter WO Improvement= 0
UNET MaxInSteps= 0
UNET DtIC= 0
UNET DtMin= 0
UNET MaxCRTS= 0
UNET WFStab= 0
UNET SFStab= 0
UNET WFX= 1
UNET SFX= 1
UNET Gravity=32.17405
UNET 1D Methodology=Finite Difference
UNET DSS MLevel= 1
UNET Pardiso=0
UNET DZMax Abort= 0
UNET Use Existing IB Tables= 0
UNET Froude Reduction=False
UNET Froude Limit= 0
UNET Froude Power= 0
UNET D1 Cores= 0
UNET WindReference=Eulerian
UNET WindDragFormulation=Hsu (1988)
UNET D2 Coriolis=0
UNET D2 Cores= 0
UNET D2 Theta= 1
UNET D2 Theta Warmup= 1
UNET D2 Z Tol= 0.01
UNET D2 Volume Tol= 0.01
UNET D2 Max Iterations= 20
UNET D2 Equation= 0
UNET D2 RampUpFraction=0.1
UNET D2 TimeSlices= 1
UNET D2 Turbulence Formulation=Non-Conservative (original)
UNET D2 Eddy Viscosity=0.3
UNET D2 Transverse Eddy Viscosity=0.1
UNET D2 Smagorinsky Mixing=0
UNET D2 BCVolumeCheck=0
UNET D2 Cores=0
UNET D2 SolverType=PARDISO (Direct)
UNET D2 Minimum Iterations= 3
UNET D2 Maximum Iterations= 30
UNET D2 Restart Number= 10
UNET D2 Relaxation Coeff=1.3
UNET D2 SOR Precondition Iterations= 10
UNET D2 ILUT Maximum Fill= 8
UNET D2 ILUT Tolerance=1E-08
UNET D2 Convergence Tolerance=0.00001
UNET D1D2 MaxIter= 0
UNET D1D2 ZTol=0.01
UNET D1D2 QTol=0.1
UNET D1D2 MinQTol=1
Write IC File= 0
Write IC File at Fixed DateTime=0
Write IC File at Sim End=0
Echo Input=False
Echo Parameters=False
Echo Output=False
Write Detailed= 0
HDF Write Warmup=0
HDF Write Time Slices=0
HDF Flush=0
HDF Compression= 1
HDF Chunk Size= 1
HDF Spatial Parts= 1
HDF Use Max Rows=0
HDF Fixed Rows= 1
Calibration Method= 0
Calibration Iterations= 20
Calibration Max Change=0.05
Calibration Tolerance=0.2
Calibration Maximum=1.5
Calibration Minimum=0.5
Calibration Optimization Method= 1
WQ AD Non Conservative
WQ ULTIMATE=-1
WQ Max Comp Step=1HOUR
WQ Output Interval=15MIN
WQ Output Selected Increments= 0
WQ Output face flow=0
WQ Output face velocity=0
WQ Output face area=0
WQ Output face dispersion=0
WQ Output cell volume=0
WQ Output cell surface area=0
WQ Output cell continuity=0
WQ Output cumulative cell continuity=0
WQ Output face conc=0
WQ Output face dconc_dx=0
WQ Output face courant=0
WQ Output face peclet=0
WQ Output face adv mass=0
WQ Output face disp mass=0
WQ Output cell mass=0
WQ Output cell source sink temp=0
WQ Output nsm pathways=0
WQ Output nsm derived pathways=0
WQ Create Restart=0
WQ Fixed Restart=0
WQ System Summary=0
WQ Write To DSS=0
Sorting and Armoring Iterations= 10
XS Update Threshold= 0.02
Bed Roughness Predictor= 0
Hydraulics Update Threshold= 0.02
Energy Slope Method= 1
Volume Change Method= 1
Sediment Retention Method= 0
Sediment TS Multiplier= 1
Warm Up Method= 0
XS Weighting Method= 0
Number of US Weighted Cross Sections= 1
Number of DS Weighted Cross Sections= 1
Upstream XS Weight=0
Main XS Weight=1
Downstream XS Weight=0
Number of DS XS's Weighted with US Boundary= 1
Upstream Boundary Weight= 1
Weight of XSs Associated with US Boundary= 0
Number of US XS's Weighted with DS Boundary= 1
Downstream Boundary Weight= 0.5
Weight of XSs Associated with DS Boundary= 0.5
Percentile Method= 0
Sediment Output Level= 3
Mass or Volume Output= 0
Output Increment Type= 1
Profile and TS Output Increment= 1
Transport Output Increment 1
XS Output Flag= 0
XS Output Increment= 10
Read HDF5 Sediment Hotstart= 0
Sediment Hotstart Type= 0
Write Gradation File= 0
Read Gradation Hotstart= 0
Write HDF5 File= 1
Write Binary Output= 1
Write DSS Sediment File= 0
DSS Sediment Output Type= 1
SV Curve= 0
Specific Gage Flag= 0
Subcell Erosion Methods= 0
Subcell Deposition Methods= 0
Advection Scheme= 1
Matrix Solver= 0
Implicit Weighting Factor= 1
Maximum Outer Loop Convergence Iterations= 5
Convergence Maximum Absolute= 0.001
Convergence RMSE= 0.0001
Grain Fractions Max Abs Error= 0.001
Max Subgrid Regions= 1
Max Subgrid Length Scale= 3.402823E+38
Initial Layer Thickness= 3.402823E+38
Min Layer Thickness= 3.402823E+38
Max Layer Thickness= 3.402823E+38
Number of Layers= 5

--- UPPERRN.f01 (steady flow) ---

Flow Title=Flow
Program Version=6.31
Number of Profiles= 1
Profile Names=F01pct
River Rch & RM=UPPERRN,Main,16336
     701
River Rch & RM=UPPERRN,Main,13630
     834
River Rch & RM=UPPERRN,Main,12512
     952
River Rch & RM=UPPERRN,Main,10630
    1090
River Rch & RM=UPPERRN,Main,6504
    1240
Boundary for River Rch & Prof#=UPPERRN,Main            , 1
Up Type= 0
Dn Type= 3
Dn Slope=0.00666
DSS Import GetInterval= 0
DSS Import GetPeak= 0
DSS Import FillOption= 0

--- UPPERRN.g01 (geometry) ---

Geom Title=Geometry
Program Version=6.30

River Reach=UPPERRN         ,Main
Reach XY= 30
  1652790.936306386604.375560516      1652615.76      386416.265
     1652220.732      386338.497     1651870.285      386004.891
     1651292.231      385709.672     1650534.589      385544.959
     1649954.585       385304.49     1648781.962      383791.559
      1648316.04      383440.182     1648296.691      383160.396
     1647867.919       382764.13     1647287.064      382434.424
     1646727.396      382406.924     1645865.159      382605.855
     1645694.042      382482.506     1645529.576      382673.577
     1644592.966       383062.37     1643722.264        383157.3
     1643043.238      383117.393     1642378.118      382926.927
     1641962.721      383050.881     1641547.928      382995.858
     1641431.229      382939.625     1641501.369      382839.252
     1641306.066      382717.1121640745.91577839 382478.83385042
      1640546.62      382577.437      1640110.06      382213.435
     1639676.741      382005.2651639434.00634142382135.759290919

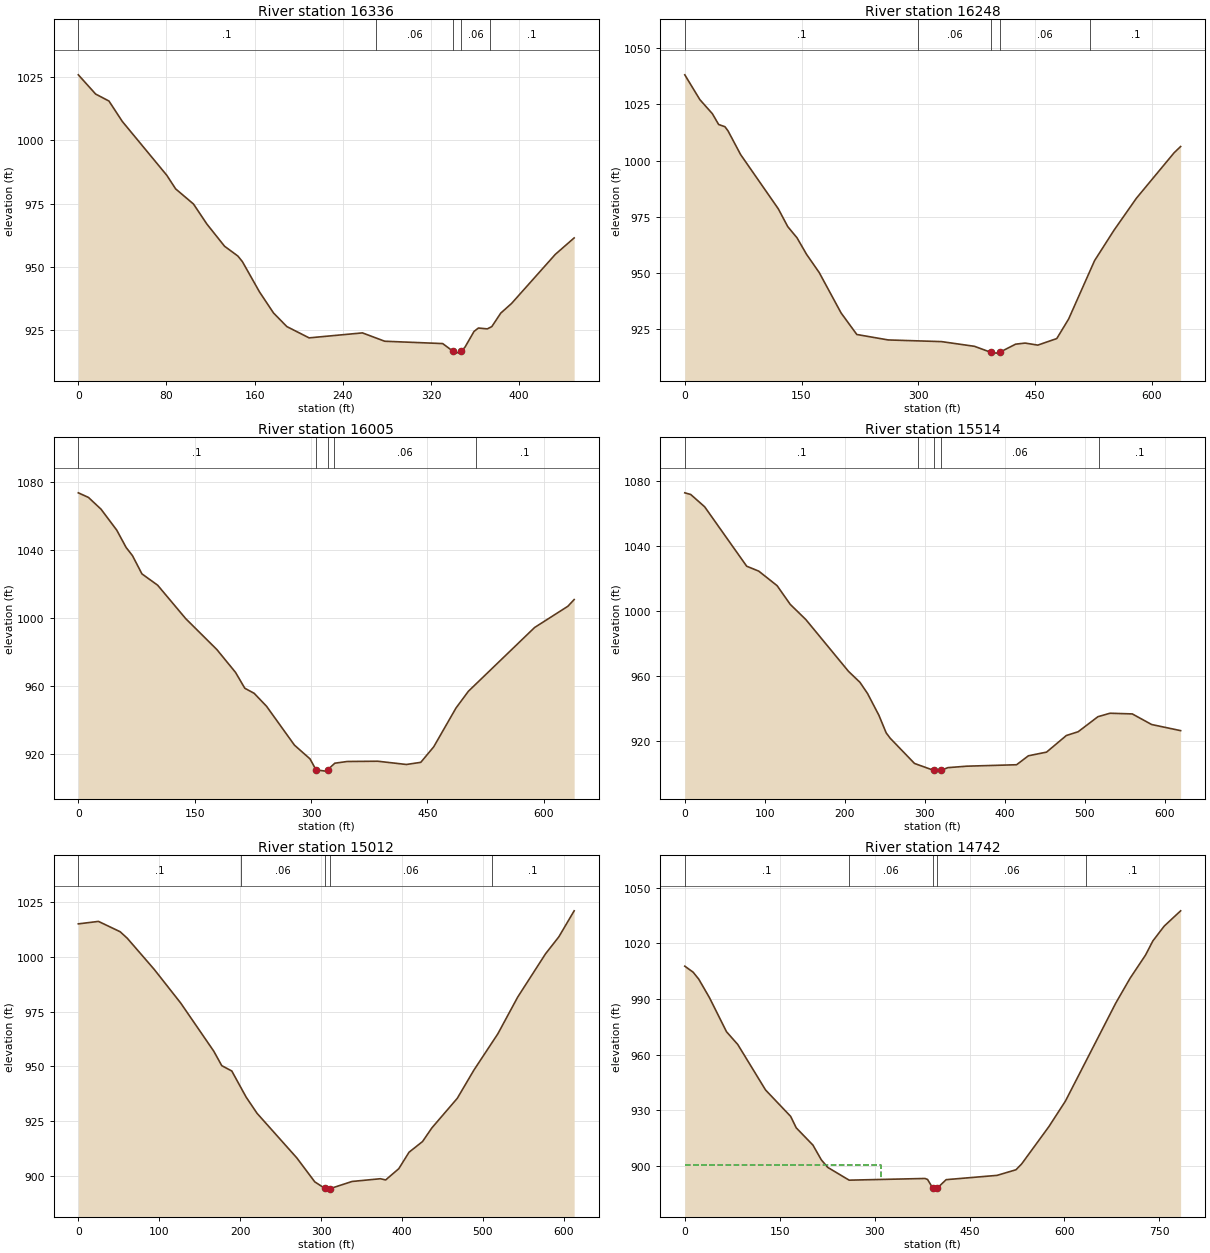
Type RM Length L Ch R = 1 ,16336   ,82,87.2,97.4
XS GIS Cut Line= 4
1652816.96244684386264.9493157941652778.72155092 386555.96176444
1652794.95455564386654.1887553671652837.47486257386691.817689491
#Sta/Elev= 30
       0 1025.98    15.7 1018.37    27.8  1015.6    39.9 1007.53    80.3  986.19
    88.3  980.82   104.5  974.83   116.6  966.93   132.7  958.11   144.8  954.23
   148.9     952   164.4  940.03   177.1   931.7   189.2  926.31   209.4  921.84
   257.8  923.81     278  920.51   330.6  919.58   339.9  916.57   342.7   915.8
   347.4  916.49   350.9  918.21     359  924.36     363  925.74   371.1   925.4
   375.2  926.31   383.3  931.64   393.1  935.46   432.8   954.9   449.9  961.41
#Mann= 5 ,-1,0
       0      .1       0     270     .06       0   339.9    .045       0
   347.4     .06       0  373.51      .1       0
Bank Sta=339.9,347.4
XS Rating Curve= 0 ,0
Exp/Cntr(USF)=0,0
Exp/Cntr=0.3,0.1

Type RM Length L Ch R = 1 ,16248   ,248.6,243.5,228.9
XS GIS Cut Line= 4
1652803.12047206386237.3703222181652757.78529193386580.622400363
 1652625.3777817386605.0890055141652509.52121025386710.151486455
#Sta/Elev= 30
       0 1038.13    19.3 1027.14    35.5 1020.82    43.5 1016.06    51.6 1015.06
    55.6 1013.19    71.8 1002.66   120.2  978.57   132.3  970.68   144.3  965.66
   156.5  958.35   172.7  950.29   200.9  932.29   221.1  922.72   261.4   920.3
     330  919.56   372.3  917.47   393.3  914.81   400.8  914.44   404.9  914.84
   425.2  918.42   437.4  918.91   453.7     918   478.1  920.91   493.4  929.63
   526.7  955.55   551.5  968.97   580.5   983.3   628.9 1003.48   637.3 1006.26
#Mann= 5 ,-1,0
       0      .1       0     300     .06       0   393.3    .045       0
   404.9     .06       0  520.88      .1       0
Bank Sta=393.3,404.9
XS Rating Curve= 0 ,0
Exp/Cntr(USF)=0,0
Exp/Cntr=0.3,0.1

Type RM Length L Ch R = 1 ,16005   ,489.2,491,493.7
XS GIS Cut Line= 6
1652599.58508867386103.7494160831652583.28525251 386197.67016001
1652574.62352443386285.984287843 1652574.5533146386462.283803999
1652533.67314701386533.5061025021652410.59005985386686.791885167
#Sta/Elev= 30
       0 1073.54      13 1070.85    29.2 1063.95    49.5 1051.61    61.7 1041.33
    69.8 1036.59      82 1025.86   102.2 1019.23   138.4  999.55   178.6  981.34
   202.6  967.95   214.6   958.6   226.6  955.64   242.6  948.01   278.6  925.13
   298.6  917.08   306.4910.6035   318.6  909.86   321.2 910.601   330.6  914.52
   346.6  915.53     386  915.68   422.9  913.77   441.4  915.03   458.1  924.17
   486.8  946.98   502.8  956.84   588.1  994.32     631 1006.82   639.1 1010.76
#Mann= 5 ,-1,0
       0      .1       0   306.4    .045       0   321.2      .1       0
  329.96     .06       0   512.5      .1       0
Bank Sta=306.4,321.2
XS Rating Curve= 0 ,0
Exp/Cntr(USF)=0,0
Exp/Cntr=0.3,0.1

Type RM Length L Ch R = 1 ,15514   ,502.4,502.5,502.1
XS GIS Cut Line= 6
1652308.93901642385998.5941145871652199.86574376386147.618750915
1652158.51018342386212.5684241651652077.53954484386368.430317178
1652025.95270576386439.7536653431651965.54272158386512.441512093
#Sta/Elev= 30
       0 1072.62     7.4 1071.61    24.8 1064.06    77.4 1027.53    92.4 1024.54
   115.4  1015.6   131.8 1004.12   151.4  994.74   204.7  962.94     219  956.22
   228.5  949.33   242.7  935.95   251.8  925.16   256.9  921.82   287.2  906.38
   311.4902.1118   315.5  901.67   319.9  902.09   328.9  903.81   352.7  904.71
   414.8  905.59   429.6  911.09   452.3  913.35     477  923.54   491.8  925.87
   516.5  935.09   531.6  937.23   559.5  936.81   583.6  930.31   619.9  926.54
#Mann= 5 ,-1,0
       0      .1       0  291.69     .06       0   311.4    .045       0
   319.9     .06       0  517.34      .1       0
Bank Sta=311.4,319.9
XS Rating Curve= 0 ,0
Exp/Cntr(USF)=0,0
Exp/Cntr=0.3,0.1

Type RM Length L Ch R = 1 ,15012   ,272.4,269.8,265.5
XS GIS Cut Line= 6
1651891.08519334385682.2184350041651849.59577501385766.289133012
1651778.34854217385912.3373973371651733.18951176   386001.572127
1651655.60961442386144.6072740111651611.09461159386227.277384251
#Sta/Elev= 30
       0 1015.08    24.9 1016.21    51.7 1011.48    60.6 1008.47    93.8  994.28
   126.5  978.92   167.5  956.85   177.3  950.28   189.7  947.84   207.5  935.86
   220.9  928.51     270  908.15   292.3  897.17   304.9894.1436   308.7  893.85
   311.6  894.13   338.4  897.35   373.3   898.6   379.9  898.05   396.1  903.18
   408.8  910.71   425.5  915.61     437  921.82   468.4  935.34     489  948.26
   518.6  964.85   543.2  981.67   577.6 1001.44   593.9 1009.12   612.9 1021.04
#Mann= 5 ,-1,0
       0      .1       0  201.25     .06       0   304.9    .045       0
   311.6     .06       0  511.35      .1       0
Bank Sta=304.9,311.6
XS Rating Curve= 0 ,0
Exp/Cntr(USF)=0,0
Exp/Cntr=0.3,0.1

Type RM Length L Ch R = 1 ,14742   ,43.1,41.6,40.2
XS GIS Cut Line= 4
1651567.51921448385504.506016385 1651445.4861325385770.304099037
1651585.90776108385914.0690997161651452.17287672386171.508752096
#Sta/Elev= 30
       0 1007.71    13.2 1004.46      22 1000.74    38.8  990.85    65.9  972.38
    83.7  965.51   127.7  940.96   167.3  926.76   176.1  920.59   202.5  911.29
   215.7  903.37   225.8   899.3   259.7   892.4   379.5  893.31   383.6  892.78
   392.1  887.97   394.9  887.57   398.5887.9734     413  892.67   493.4  894.98
   523.3     898   532.2  901.11   575.4  921.28   601.5  935.03     681  987.81
   703.6 1001.18     728 1013.66   739.6 1021.29   757.6 1029.31   783.5 1037.53
#Mann= 5 ,-1,0
       0      .1       0     260     .06       0   392.1    .045       0
   398.5     .06       0  633.44      .1       0
#XS Ineff= 2 , 0
          309.42  900.36
Permanent Ineff=
       F       F
Bank Sta=392.1,398.5
XS Rating Curve= 0 ,0
Exp/Cntr(USF)=0,0
Exp/Cntr=0.3,0.1

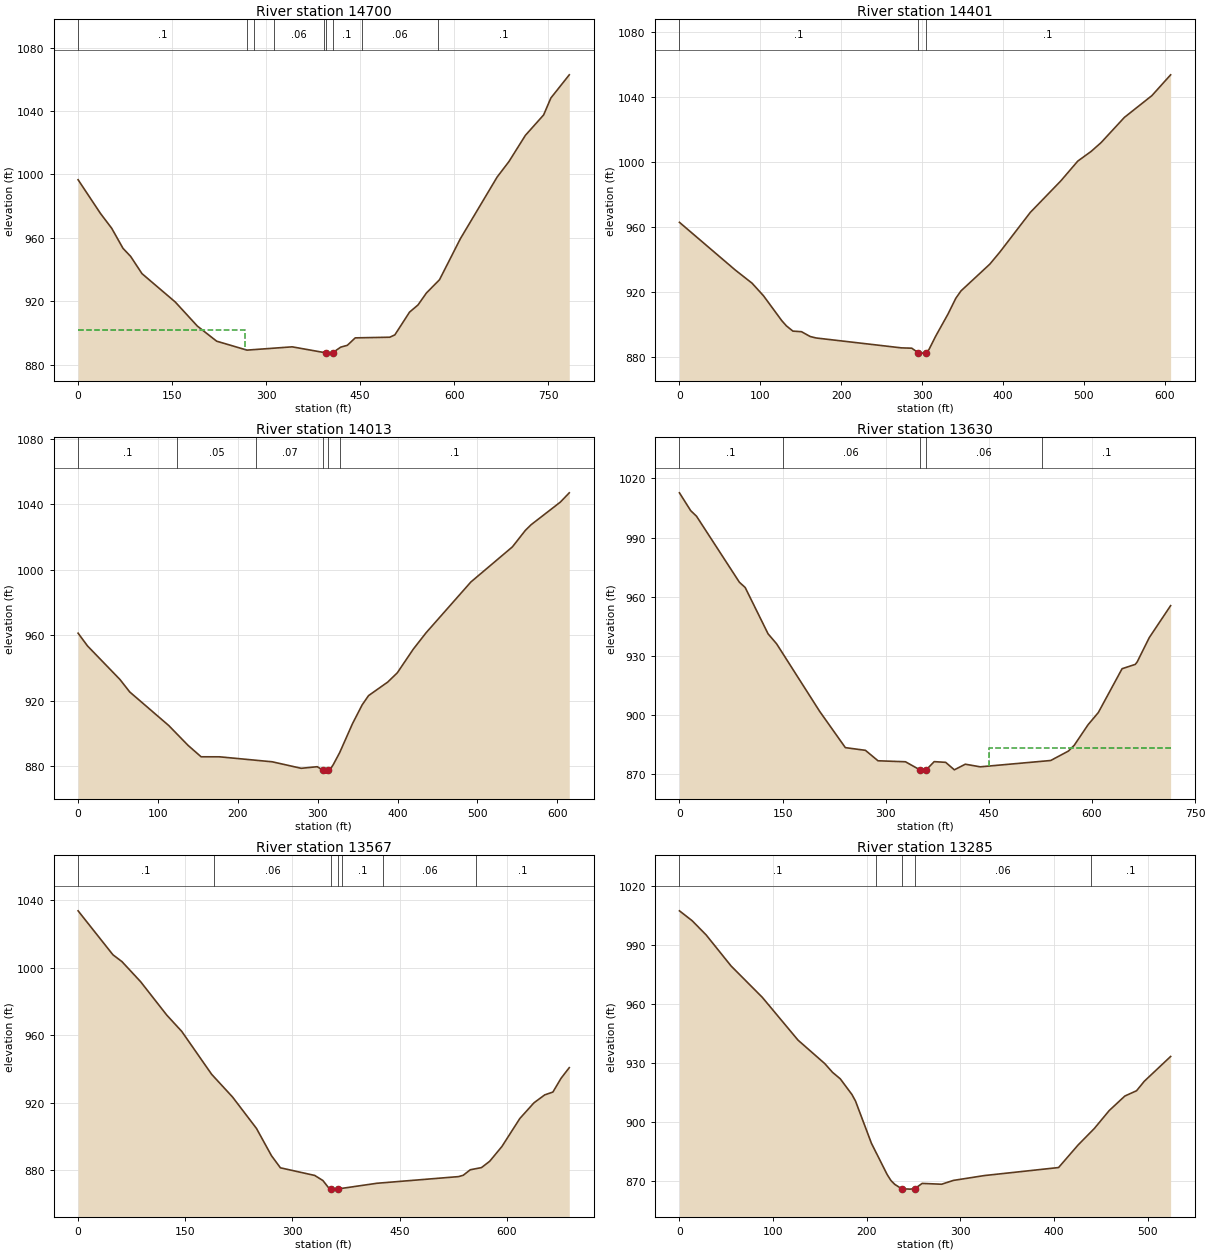
Type RM Length L Ch R = 1 ,14700   ,293.9,298.8,301.9
XS GIS Cut Line= 4
1651522.38369101385503.6701733581651400.35060904385769.468256009
1651540.77223761385913.2332566891651407.03735325386170.672909069
#Sta/Elev= 30
       0  996.64    35.5  975.47    53.6  966.01    71.7  953.31    83.8  948.27
   101.9  937.39     155  919.48   190.2  904.31     221  894.76   269.4  889.12
   341.5  891.19   395.2   887.4     403  887.22     406887.4533   418.9  890.99
   429.5  892.16   442.1  896.85   497.2  897.26   505.3  898.75   528.7   913.1
   542.2  917.62   555.7  925.21   576.5  933.54   609.8  959.44   668.4  998.32
   687.3 1008.14   713.5 1024.65   742.6 1037.55   754.1  1048.2   783.5 1062.85
#Mann= 9 ,-1,0
       0      .1       0     270     .06       0     280      .1       0
  312.47     .06       0  392.47      .1       0   395.2    .045       0
     406      .1       0  452.47     .06       0  573.44      .1       0
#XS Ineff= 2 , 0
          266.28  901.78
Permanent Ineff=
       F       F
Bank Sta=395.2,406
XS Rating Curve= 0 ,0
Exp/Cntr(USF)=0,0
Exp/Cntr=0.3,0.1

Type RM Length L Ch R = 1 ,14401   ,388.2,388,386.4
XS GIS Cut Line= 3
1651402.02229509385447.668690535 1651254.9139223385613.165609922
1651142.91095666385982.608227947
#Sta/Elev= 30
       0  962.94    69.1  933.52    89.8  925.44     104  917.65   126.6  902.33
   132.3  899.13   140.3  895.91     151  895.53   161.7  892.58   169.1  891.67
   274.5  885.58   287.3  885.38     295882.6852   300.1  882.34   304.4  882.67
   308.5  884.46   316.9  892.77   332.2  906.47   341.8  916.12   348.2  920.68
   383.8  937.14   396.3  944.61   433.9  969.03   471.6  988.42   492.6 1000.64
   509.2 1006.65   521.5 1012.07   550.3 1027.59   584.4 1041.05   607.5 1053.83
#Mann= 3 ,-1,0
       0      .1       0     295    .045       0   304.4      .1       0
Bank Sta=295,304.4
XS Rating Curve= 0 ,0
Exp/Cntr(USF)=0,0
Exp/Cntr=0.3,0.1

Type RM Length L Ch R = 1 ,14013   ,375.7,383.6,389.6
XS GIS Cut Line= 6
1650897.63048734385324.8953307571650881.05604543385417.808530763
1650866.12923801385504.8526480051650854.79953626385579.800004676
1650846.24673185385679.6987550111650838.14963518385935.747455508
#Sta/Elev= 30
       0  961.28    11.8  953.49    52.5  932.97    64.6  925.42   113.4  904.95
   137.7  892.79     154  885.83   177.2  885.81   243.1  882.77   279.3   878.8
   299.4  879.78   306.8877.5464   311.4  877.08   313.4  877.52   315.4  877.98
   319.5  881.11   327.5  888.41   343.5  906.03   355.6   917.5   363.6  923.17
   387.6  931.43   399.6  937.08   419.6  951.52   435.6  961.51   491.7  992.52
   543.7 1013.96   559.9 1024.02   567.2 1027.51   603.7 1041.28   614.9 1046.95
#Mann= 6 ,-1,0
       0      .1       0  124.38     .05       0  222.69     .07       0
   306.8    .045       0   313.4     .07       0  328.49      .1       0
Bank Sta=306.8,313.4
XS Rating Curve= 0 ,0
Exp/Cntr(USF)=0,0
Exp/Cntr=0.3,0.1

Type RM Length L Ch R = 1 ,13630   ,63.1,62.6,63
XS GIS Cut Line= 4
1650642.11096333  385208.75173241650554.84895129385509.655222195
1650435.99207282385473.5468034191650273.50418833385697.719903316
#Sta/Elev= 30
       0  1012.7    16.4 1003.64    24.8 1000.85    87.2  967.34    95.6  964.68
   128.9  941.18   141.4  936.07   203.9  901.87   241.3  883.45   270.5  882.08
   288.8  876.78   328.7  876.28   349.6  872.21   353.8  871.53   358.9872.1791
   370.5  876.34   387.2  875.99   399.8  872.19   415.8  875.04   437.5  873.71
     540  876.92   565.6  881.68   574.2  884.64   594.2  895.01   609.2  901.23
   643.8  923.48     663  925.68   665.8  926.95   683.3  939.24   714.4  955.47
#Mann= 5 ,-1,0
       0      .1       0     150     .06       0   349.6    .045       0
   358.9     .06       0  527.52      .1       0
#XS Ineff= 2 , 0
                           450.9           883.2
Permanent Ineff=
       F       F
Bank Sta=349.6,358.9
XS Rating Curve= 0 ,0
Exp/Cntr(USF)=0,0
Exp/Cntr=0.3,0.1

Type RM Length L Ch R = 1 ,13567   ,285.9,281.7,276.6
XS GIS Cut Line= 4
1650630.82708246385165.8729851051650542.47407328385452.620450344
1650425.78828201385439.7888165641650262.22030747385654.841156021
#Sta/Elev= 30
       0 1033.63    48.8 1007.58    61.4 1003.55    87.5  991.66   124.2  971.83
   145.1  962.22     187  936.77   216.3   923.3   249.7  904.74   270.7   888.6
   283.2  881.41   331.3  876.88   342.7  873.87   350.7  869.58   354.7  868.91
   358.8  868.78   363.9   868.9   418.4  872.25   532.5  876.19   539.1  876.97
     549  880.25   564.7  881.53   576.2  885.28   593.3  894.03   618.4  910.62
   638.2  919.92   653.2   924.6   664.7  926.29   676.1  934.44   687.6  940.73
#Mann= 7 ,-1,0
       0      .1       0     190     .06       0   354.7    .045       0
   363.9     .06       0  370.05      .1       0  427.44     .06       0
  557.44      .1       0
Bank Sta=354.7,363.9
XS Rating Curve= 0 ,0
Exp/Cntr(USF)=0,0
Exp/Cntr=0.3,0.1

Type RM Length L Ch R = 1 ,13285   ,403.1,407.3,411.4
XS GIS Cut Line= 2
1650284.03581048385127.5077901561650138.09761793385631.521135562
#Sta/Elev= 30
       0 1007.35    13.6 1002.31    28.5   995.1    55.2  979.28    88.5  963.36
   126.7  941.57   155.2  929.67   163.5  925.22   171.8  921.91   184.3   913.9
   188.1  910.57   205.1  889.11   221.8  873.31   225.9   870.2   230.1   868.2
   237.4865.9916   246.2  865.81   251.2  865.98   259.3  868.72   280.1   868.3
   292.6  870.24   325.9  872.72     405  876.79   425.8  888.23   443.2  896.65
   459.1  905.77   475.8  913.16   488.3  915.85   496.6  920.69   524.7  933.27
#Mann= 5 ,-1,0
       0      .1       0     210     .06       0   237.4    .045       0
   251.2     .06       0     440      .1       0
Bank Sta=237.4,251.2
XS Rating Curve= 0 ,0
Exp/Cntr(USF)=0,0
Exp/Cntr=0.3,0.1

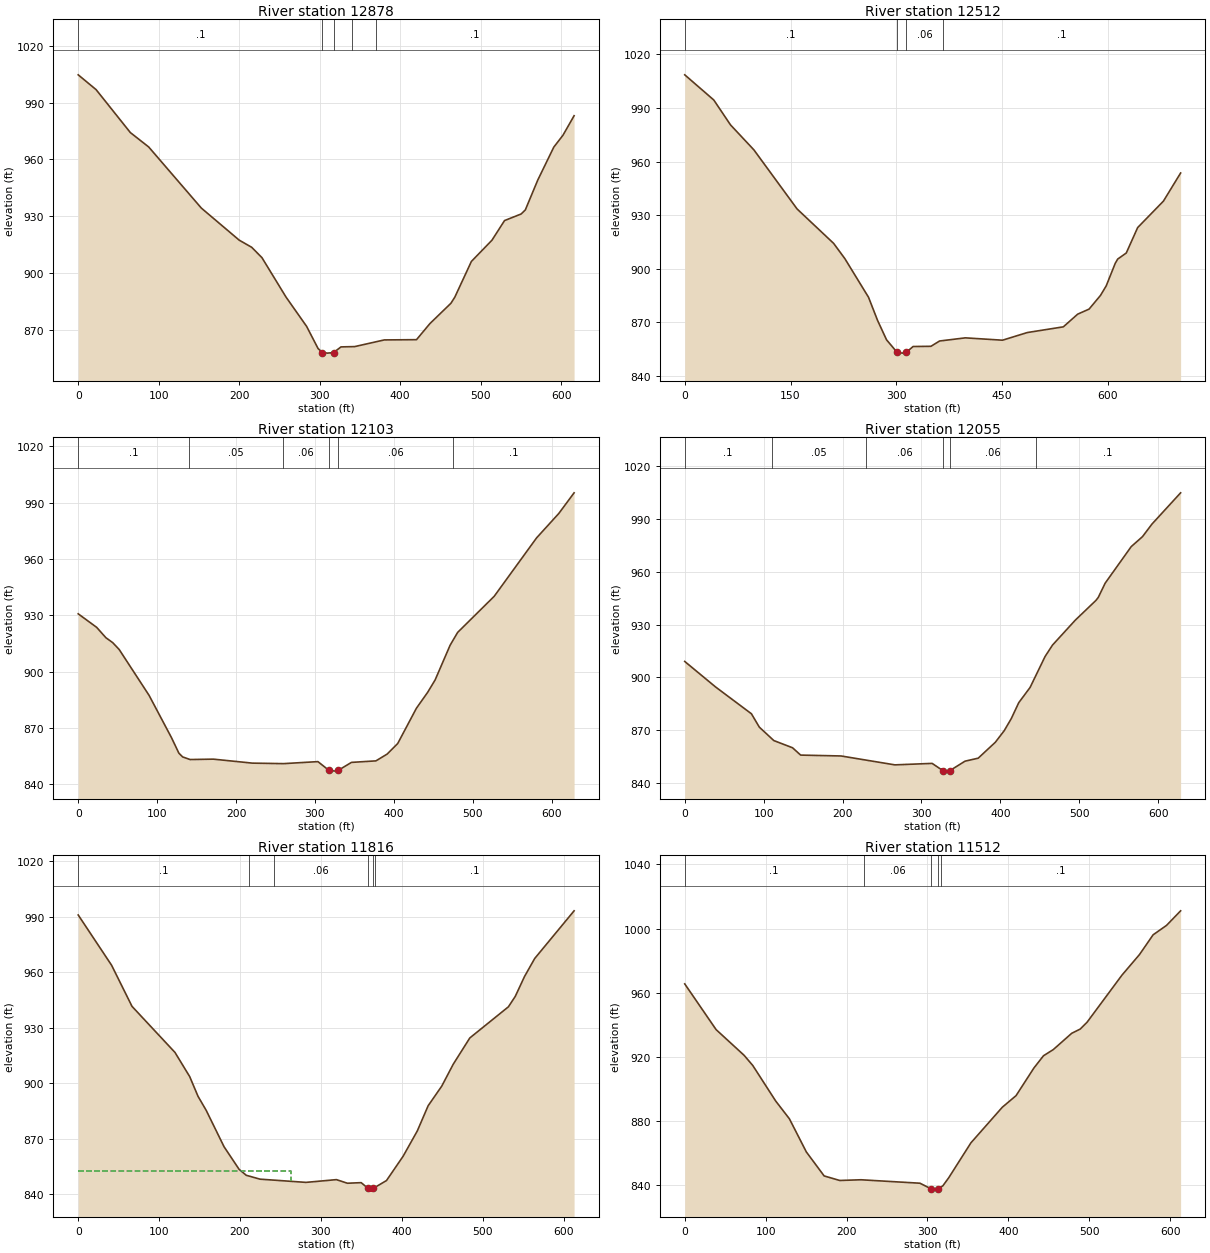
Type RM Length L Ch R = 1 ,12878   ,365.2,365.9,366.9
XS GIS Cut Line= 2
1650091.45757701385020.6870512791649613.02102824385408.852553114
#Sta/Elev= 30
       0 1004.69    22.2  996.88    64.8  974.16    87.6  966.55     153  934.25
     200  917.32   215.5  913.55   228.3  908.05   258.2  887.22   283.8  871.73
     298  860.04   303.4  857.89   309.4   857.6   317.2  857.88   326.5  860.89
   343.5  861.05   380.3  864.58   420.3  864.71     437  873.22     463  883.92
   467.9  887.17   488.5  906.06     514  917.25   529.7  927.66   550.3  931.14
   555.5  933.28     571  949.09   590.9  966.49   602.3  972.77   616.1  983.07
#Mann= 5 ,-1,0
       0      .1       0   303.4    .045       0   317.2      .1       0
     340     .06       0     370      .1       0
Bank Sta=303.4,317.2
XS Rating Curve= 0 ,0
Exp/Cntr(USF)=0,0
Exp/Cntr=0.3,0.1

Type RM Length L Ch R = 1 ,12512   ,413.2,409.2,404.5
XS GIS Cut Line= 6
1649890.82705475384762.3282144221649811.84099226384812.854360089
  1649737.485826384858.9812363391649524.57155368384990.005580589
1649450.05070534385035.863428503 1649267.9707852385006.312296258
#Sta/Elev= 30
       0 1008.49    41.2  994.41    64.9   980.5    98.1  966.51   159.3  933.49
   211.1  914.24     227  905.74   260.6  884.11   273.5   871.1   286.2  860.28
   301.3 853.227   308.4  852.85     314  853.22   323.8  856.55   349.1  856.66
   361.4  859.63   397.9  861.39   450.6  860.08   485.8  864.36   536.9  867.55
   557.2  874.64   573.4  877.47   589.5  885.09   597.7  890.47   610.5  903.09
     614  905.46   626.1  908.83   642.3  923.07   678.8  937.85   703.2  953.58
#Mann= 4 ,-1,0
       0      .1       0   301.3    .045       0     314     .06       0
  366.26      .1       0
Bank Sta=301.3,314
XS Rating Curve= 0 ,0
Exp/Cntr(USF)=0,0
Exp/Cntr=0.3,0.1

Type RM Length L Ch R = 1 ,12103   ,47.8,48.2,49.7
XS GIS Cut Line= 4
1649655.97778755384388.0401469391649431.20288067384530.217045867
1649400.05936948384665.6236162741649211.84423661384786.135463937
#Sta/Elev= 30
       0  930.85    23.4  923.64    35.1  918.12    43.7  915.51    51.9  911.87
    89.8  887.44   118.2  864.92   127.6  856.63   132.4  854.64   141.8  853.26
   171.3  853.47   220.6  851.35   260.2  851.08   303.8  852.15   317.6  847.54
   325.8  847.09   329.6847.5391   346.3  851.74   377.3  852.55   391.5  856.17
   404.9   861.8   428.6  880.58   442.8  889.03   452.3  895.64   471.3  914.13
   480.8  920.93   527.2   940.2   580.9  971.29   609.1  984.32   628.4  995.27
#Mann= 6 ,-1,0
       0      .1       0     140     .05       0     260     .06       0
   317.6    .045       0   329.6     .06       0  474.91      .1       0
Bank Sta=317.6,329.6
XS Rating Curve= 0 ,0
Exp/Cntr(USF)=0,0
Exp/Cntr=0.3,0.1

Type RM Length L Ch R = 1 ,12055   ,234.9,238.8,240.5
XS GIS Cut Line= 4
1649627.54240776   384342.0019131649402.76750089384484.178811928
1649371.62398969384619.5853823361649183.40885682384740.097229999
#Sta/Elev= 30
       0  909.01    39.1  894.49    84.5  879.25    94.5  871.65   112.9     864
   136.6  859.91   146.9  855.74   198.1  855.24   266.3  850.18   313.5  851.02
   327.2 846.896   331.3  846.62   336.1  846.95   355.2  852.28   371.9  853.99
   393.6  863.04   404.9  869.66   413.8  876.49   423.3  885.57   437.6  894.19
   456.6   911.8   466.1  918.35     495  932.53   521.1  943.74     524   945.4
   532.8  953.55   565.8  974.33   580.1  980.01   592.1  987.16   628.4 1004.93
#Mann= 6 ,-1,0
       0      .1       0     110     .05       0     230     .06       0
   327.2    .045       0   336.1     .06       0  444.91      .1       0
Bank Sta=327.2,336.1
XS Rating Curve= 0 ,0
Exp/Cntr(USF)=0,0
Exp/Cntr=0.3,0.1

Type RM Length L Ch R = 1 ,11816   ,304,303.9,303.1
XS GIS Cut Line= 6
1649524.85737065384133.4503796871649450.30896332384190.782614115
1649381.74971724384245.4094733621649324.48802074384293.872631031
1649120.83980599384459.5045176181649049.16573674384519.934842947
#Sta/Elev= 30
       0     991    41.3  963.78    66.5  941.55   119.6  916.63   137.8  903.55
   148.1  892.88   158.2  885.28   180.3  865.57   198.9  853.34   207.8  850.11
   224.8  848.02   281.6  846.28   319.2  847.77   332.8  845.82   349.8  846.13
   358.4  843.02   361.2  842.63   364.6843.0131   381.1  847.27   401.7  860.47
   419.2  874.14   432.6  887.77   449.4  898.37   463.6  910.23   484.1  924.45
   531.8   941.3   540.3  946.95   551.7  957.68   564.3  967.45     613  993.25
#Mann= 6 ,-1,0
       0      .1       0  211.71     .05       0  241.71     .06       0
   358.4    .045       0   364.6     .06       0  366.72      .1       0
#XS Ineff= 2 , 0
          262.69  852.31
Permanent Ineff=
       F       F
Bank Sta=358.4,364.6
XS Rating Curve= 0 ,0
Exp/Cntr(USF)=0,0
Exp/Cntr=0.3,0.1

Type RM Length L Ch R = 1 ,11512   ,499.3,498.2,497.7
XS GIS Cut Line= 6
1649273.49594034383919.0395466691649205.28183793383983.350769758
1649014.29009393384163.4294778411648961.10647325384216.349975675
1648899.65712109384278.7589715871648831.51060385384343.526230499
#Sta/Elev= 30
       0  965.47    38.8  936.92    73.4  920.89    84.1  914.54   112.4  892.39
   129.4  881.24   150.3  860.59   172.3  845.62   191.6  842.78   217.9  843.22
   290.7  841.07   304.3  837.62   307.6  837.38   313.3  837.65     319  839.42
   326.3  844.49   353.7  866.26   392.5  888.48   409.5  895.72   431.5  912.93
   443.4  920.61   455.5  924.46   478.3  934.64   488.7  937.24   497.2  941.49
   540.3  970.87   562.1   983.8   578.9  996.09   595.5 1001.99   612.9 1011.07
#Mann= 5 ,-1,0
       0      .1       0  221.25     .06       0   304.3    .045       0
   313.3     .06       0  316.25      .1       0
Bank Sta=304.3,313.3
XS Rating Curve= 0 ,0
Exp/Cntr(USF)=0,0
Exp/Cntr=0.3,0.1

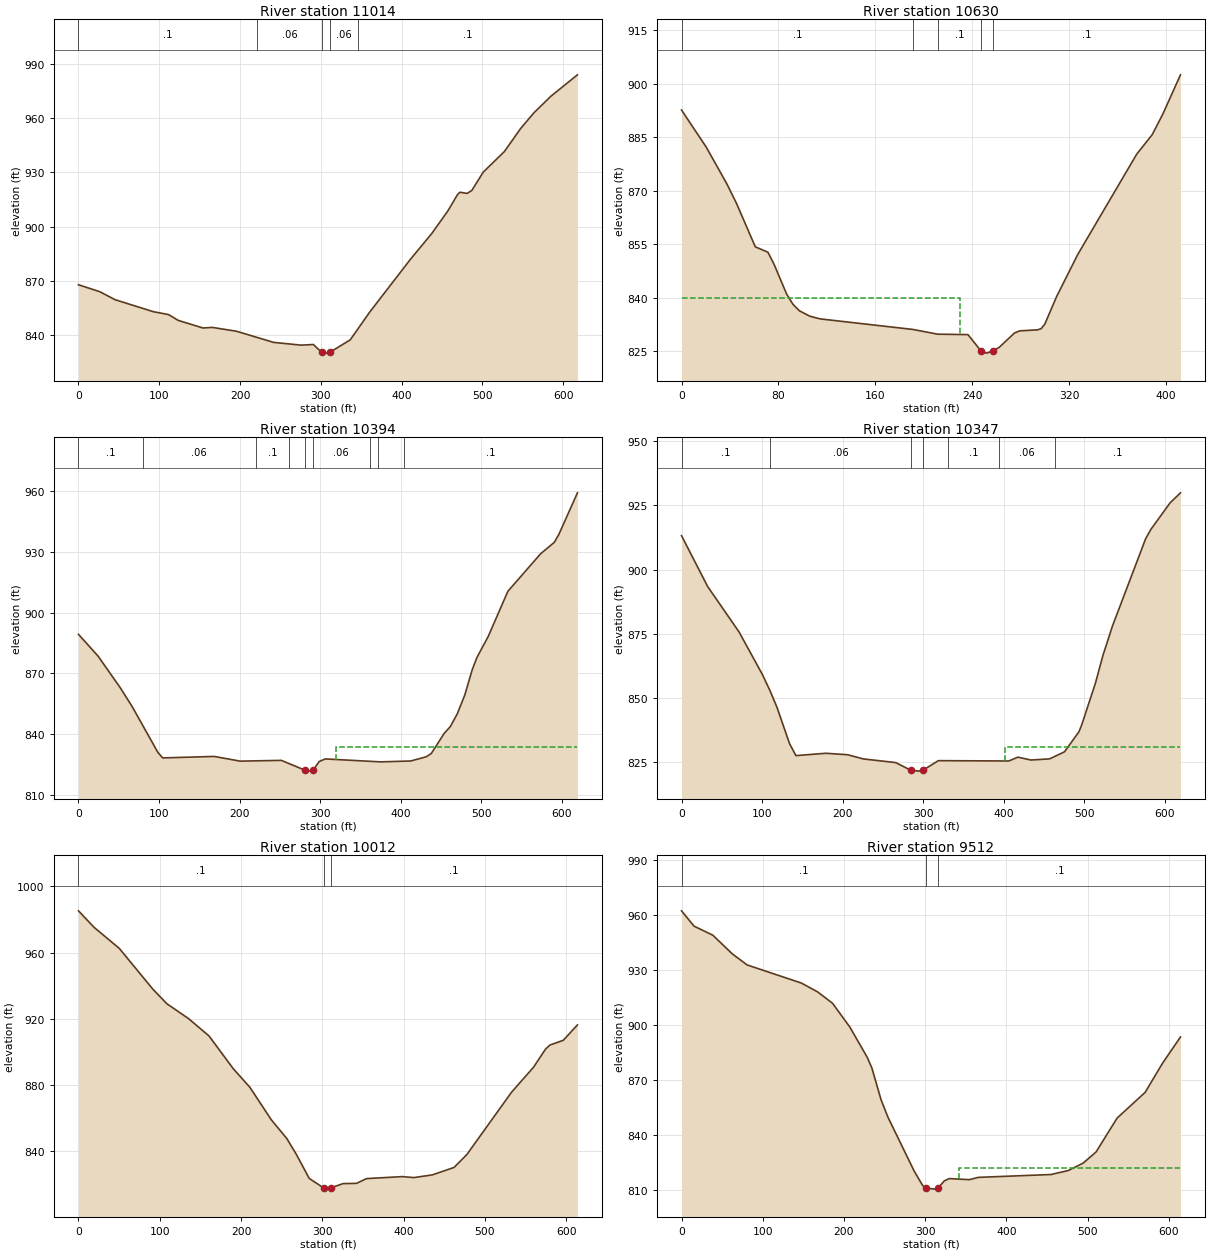
Type RM Length L Ch R = 1 ,11014   ,383.5,383.6,383.6
XS GIS Cut Line= 6
1648924.57078518 383508.310053171648763.98875725383707.959916338
1648702.24970751 383786.704837591648661.58738726 383850.51835826
1648613.35618451383925.5310035051648558.78116243384004.909781754
#Sta/Elev= 30
       0  867.91    26.3  864.07    45.4  859.63    92.7  853.01   111.4  851.43
   123.5   848.2   154.1     844   165.5  844.33   195.4  842.22   241.6  836.04
   275.5  834.53   290.7  834.87   301.1830.5029     305  830.11   310.7  830.48
   336.3  837.43   360.3  852.72   410.6  881.86   437.4  896.33   456.9  908.57
   469.2  917.82   472.1  919.06   480.8   918.4   486.7  919.98     501   930.2
   527.1  941.54   547.2  954.27   563.6  962.93   584.6   972.1   617.5  983.95
#Mann= 5 ,-1,0
       0      .1       0  221.22     .06       0   301.1    .045       0
   310.7     .06       0  346.22      .1       0
Bank Sta=301.1,310.7
XS Rating Curve= 0 ,0
Exp/Cntr(USF)=0,0
Exp/Cntr=0.3,0.1

Type RM Length L Ch R = 1 ,10630   ,225.4,236.2,240.2
XS GIS Cut Line= 3
1648585.67521892383333.289830907 1648403.6724041383556.659939751
1648290.84528553383607.298882732
#Sta/Elev= 30
       0  892.68    20.5  882.23    37.5  871.93    45.5  866.43    60.9  854.33
    71.3  852.83    76.4  849.42    86.7  841.14    91.9  838.26    97.2  836.43
   105.8   834.9   114.3  834.14   191.1  831.17   211.4  829.85   236.4  829.73
   247.2825.1475   251.9  824.54     257  825.13   262.2  826.16   274.8  830.18
   279.2  830.79   293.8  831.06   296.8   831.4   299.8  832.65   309.6  840.41
     327  852.17   375.7  880.31   388.5  885.78   397.3  891.58   411.8  902.54
#Mann= 5 ,-1,0
       0      .1       0   191.1     .06       0   211.4      .1       0
   247.2    .045       0     257      .1       0
#XS Ineff= 2 , 0
             230     840
Permanent Ineff=
       F       F
Bank Sta=247.2,257
XS Rating Curve= 0 ,0
Exp/Cntr(USF)=0,0
Exp/Cntr=0.3,0.1

Type RM Length L Ch R = 1 ,10394   ,48.1,47.1,51.2
XS GIS Cut Line= 4
1648520.98096862 383270.100098051648313.35756066383393.470528866
  1648244.149758383268.5955806011648086.17542586383443.119604682
#Sta/Elev= 30
       0  889.31    24.3  878.56    51.8  862.96    66.1     854    98.7  830.91
   104.6  828.24   168.5  828.97   200.9  826.64   251.9  827.03   281.4  822.16
   288.3  821.71   291.3 822.145     299  826.48   306.6  827.74   375.2  826.28
   412.6  826.72     432  828.81   438.2  830.44   454.3  840.41   461.8   843.7
   470.5  850.06   479.7  859.22     489  871.79   494.7  877.73   508.9  888.27
   533.3  910.57     574  929.13     591  934.78   596.7  938.74   619.7  959.23
#Mann= 9 ,-1,0
       0      .1       0      80     .06       0     220      .1       0
  261.51     .06       0   281.4    .045       0   291.3     .06       0
  361.51      .1       0  371.51     .06       0  404.28      .1       0
#XS Ineff= 2 , 0
                          320.06          833.46
Permanent Ineff=
       F       F
Bank Sta=281.4,291.3
XS Rating Curve= 0 ,0
Exp/Cntr(USF)=0,0
Exp/Cntr=0.3,0.1

Type RM Length L Ch R = 1 ,10347   ,344.9,335.1,322.7
XS GIS Cut Line= 4
1648538.28291928383227.9736094791648330.65951132383351.344040294
1648261.45170867 383226.469092031648103.47737653383400.993116111
#Sta/Elev= 30
       0  913.22    32.4  893.42    71.6  875.61   100.2  859.23     110  852.73
   118.7  846.19   134.2  832.12   142.1  827.47   179.3  828.38   206.3  827.81
   225.9  826.17     266  824.75   285.1821.7145     295  821.42   299.6  821.71
     319   825.5   406.5  825.37   417.8  826.87     434  825.75   457.2   826.2
   475.7  828.96   493.6  836.75   497.1  839.49   514.1  855.73   523.4  866.51
   535.3  878.04   576.4  911.98     583  915.68   606.8  925.99   619.7  929.91
#Mann= 7 ,-1,0
       0      .1       0     110     .06       0   285.1    .045       0
   299.6     .06       0  331.51      .1       0  394.28     .06       0
  464.28      .1       0
#XS Ineff= 2 , 0
                          402.08          831.01
Permanent Ineff=
       F       F
Bank Sta=285.1,299.6
XS Rating Curve= 0 ,0
Exp/Cntr(USF)=0,0
Exp/Cntr=0.3,0.1

Type RM Length L Ch R = 1 ,10012   ,501.6,499.9,496.2
XS GIS Cut Line= 6
1648362.46167317382805.886917338  1648199.173942383003.252992421
1648135.00281051383079.9542825821648086.86904851383137.509941757
1648028.64081851383203.0534458461647959.37947409383268.003447175
#Sta/Elev= 30
       0  985.26      19  975.36    50.2  962.56    91.6  937.86   108.7  929.15
   135.5   920.1   160.6  909.66   190.3  889.93   210.8  878.69   237.1  859.08
   256.2  847.75   267.8  838.31   283.9  823.57   301.5817.8809   304.8  817.12
   310.4817.8746   325.6  820.47     342   820.6   354.4  823.49   398.4  824.68
   412.6   824.1   435.3  825.72     462  830.21   477.8  838.03   532.7  875.65
   559.9  890.84   574.4  901.63   579.9  904.16   596.4  907.04   613.8  916.34
#Mann= 3 ,-1,0
       0      .1       0   301.5    .045       0   310.4      .1       0
Bank Sta=301.5,310.4
XS Rating Curve= 0 ,0
Exp/Cntr(USF)=0,0
Exp/Cntr=0.3,0.1

Type RM Length L Ch R = 1 ,9512    ,498,499.9,503.4
XS GIS Cut Line= 6
1647893.50624625382438.1245295111647804.53956068382678.371096253
1647769.54750468382772.0493865911647743.36514235382842.348130509
1647712.63127993382924.3998036681647674.37512285383011.957699418
#Sta/Elev= 30
       0  962.08    15.4  953.75    38.6  948.81    62.3  938.75    80.8  932.64
   147.6  922.78   167.9  917.88     186  911.77   207.3  898.82   228.6  882.45
   234.4  876.58   245.7  859.31   254.2  849.79   286.4  820.56   296.9  812.65
   300.7811.2589   311.1  810.65   315.9811.2097   323.5  815.11   329.7  816.38
   354.6   815.8   365.2  817.04   454.9   818.6   476.3  820.78   494.5  824.78
   510.4  830.83   536.4  849.31     571  863.35   592.2  879.08   614.4  893.42
#Mann= 3 ,-1,0
       0      .1       0   300.7    .045       0   315.9      .1       0
#XS Ineff= 2 , 0
                          341.19          822.37
Permanent Ineff=
       F       F
Bank Sta=300.7,315.9
XS Rating Curve= 0 ,0
Exp/Cntr(USF)=0,0
Exp/Cntr=0.3,0.1

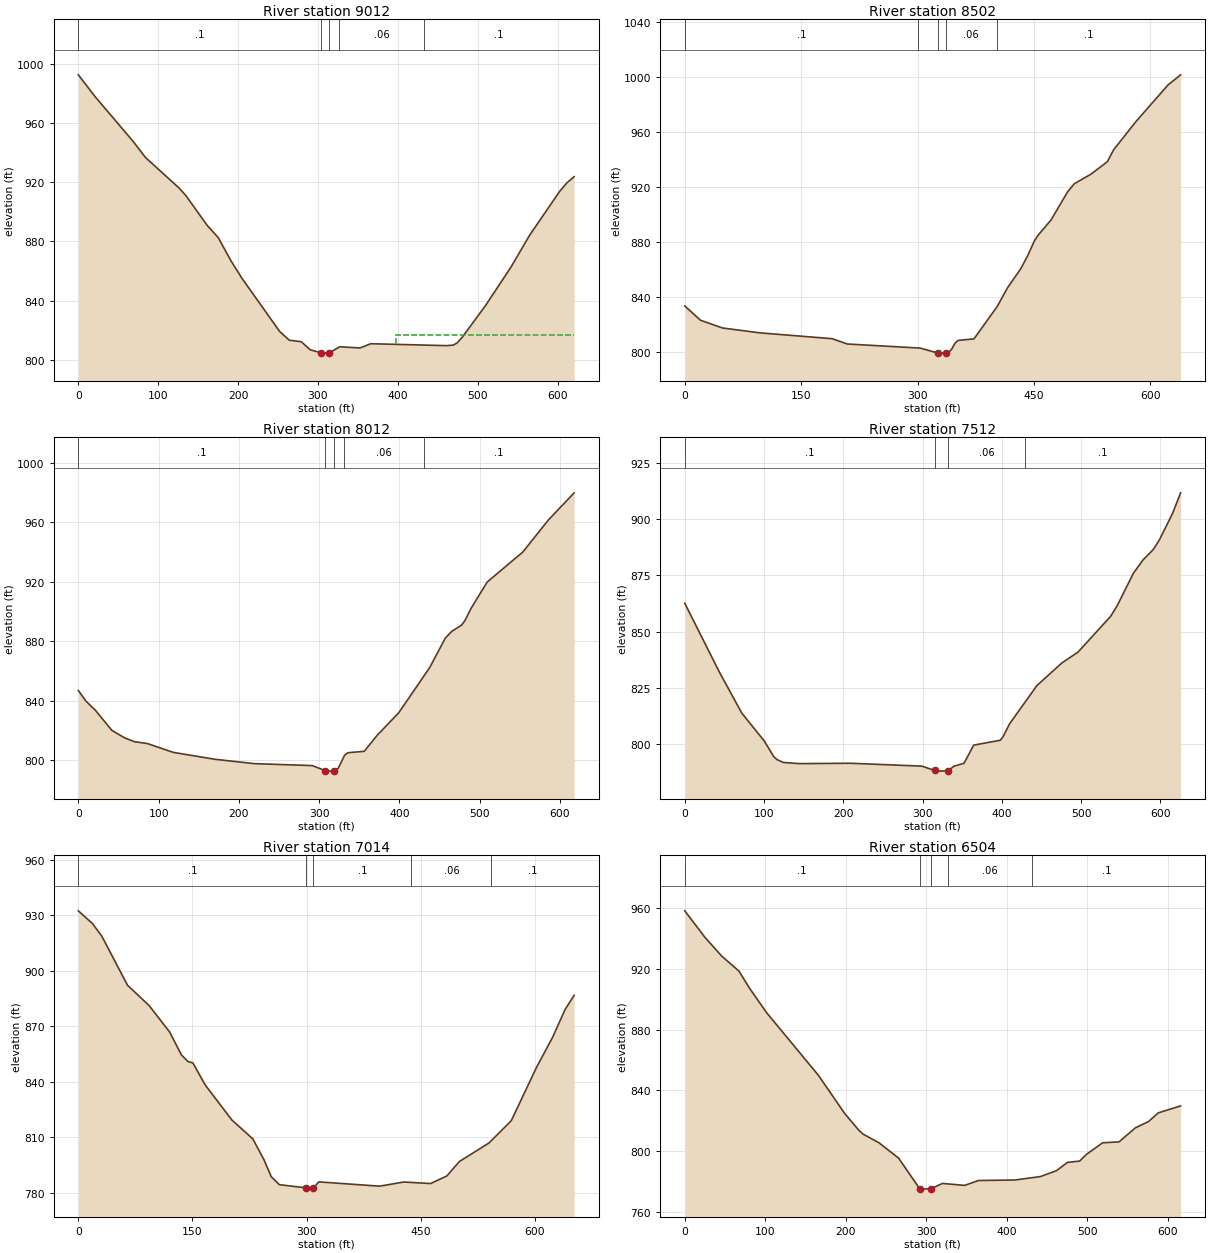
Type RM Length L Ch R = 1 ,9012    ,511.4,510.7,504.5
XS GIS Cut Line= 6
1647581.63515083382272.3581287561647520.68579768 382344.49085851
1647323.44242576382517.699829668 1647272.9887865 382574.19742009
1647221.57287884382648.7185965031647171.40204743382732.384111583
#Sta/Elev= 30
       0  992.36    20.9  977.71    68.3  947.67      84  936.66   126.1  916.02
   134.6  910.98   161.2  890.89   175.1  882.62   191.2  866.83   205.4  854.71
   252.1  819.24   264.2  813.34   279.1  812.36   290.4  806.87   304.3  804.82
   310.3  804.64     314 804.806   327.3  808.92   352.8  808.14   366.1  810.99
   460.9  809.69   469.5  810.06   474.4  811.58     481  815.55   509.8  836.71
   541.7  862.67     565  884.12   602.3   913.5   611.6  919.45   620.8  923.67
#Mann= 5 ,-1,0
       0      .1       0   304.3    .045       0     314      .1       0
  326.93     .06       0  432.68      .1       0
#XS Ineff= 2 , 0
                          398.06          816.57
Permanent Ineff=
       F       F
Bank Sta=304.3,314
XS Rating Curve= 0 ,0
Exp/Cntr(USF)=0,0
Exp/Cntr=0.3,0.1

Type RM Length L Ch R = 1 ,8502    ,489.6,489.3,489.3
XS GIS Cut Line= 6
1646888.83240259382100.5405590091646929.45404051382377.866447926
1646909.59089126382477.6303559991646879.91969076 382546.51145184
1646849.53786176382628.6540040821646826.93488859382720.332626507
#Sta/Elev= 30
       0  833.28    20.2  822.94    48.6   817.3    97.1  813.74     190  809.52
   209.5  805.66   303.4   802.7   326.1799.1094   327.9  799.03     336  799.11
   340.1  799.54   344.2  802.11   348.3  806.32   352.3  808.26   372.7  809.41
   402.6  832.89   415.8  846.45   433.1  860.48   441.8  869.73   450.5  880.56
   455.4  884.75     472  895.81   493.3   916.2     502  922.16   523.1  928.96
   544.5  938.13   552.7  946.87   581.5  967.38   622.7  993.91     639  1001.3
#Mann= 5 ,-1,0
       0      .1       0  300.29     .06       0   326.1    .045       0
     336     .06       0  402.01      .1       0
Bank Sta=326.1,336
XS Rating Curve= 0 ,0
Exp/Cntr(USF)=0,0
Exp/Cntr=0.3,0.1

Type RM Length L Ch R = 1 ,8012    ,500.7,500,496.3
XS GIS Cut Line= 6
1646451.71057342382167.0568301681646463.70923708 382262.55926384
1646469.03927892382351.4957657611646432.83593926382598.873551846
1646423.80380508382686.1893220841646418.05316043382780.391233429
#Sta/Elev= 30
       0  846.87     9.6  839.68    21.6  833.37    41.8  820.07    57.9  814.95
      70  812.47    86.2  811.17   118.3  805.28   170.3  800.63   219.4  797.71
   291.3   796.4   307.5  793.04     315  792.68   318.5  792.98   323.7  794.57
   331.8   803.5   335.9  805.06   356.1  805.99   372.3  816.81     399  831.83
   437.6  862.21   457.2  882.16   465.2  886.62   477.3  890.76   481.3  893.61
   489.3  902.18   509.4  919.83   553.6  939.88   585.6  961.51   617.6   979.7
#Mann= 5 ,-1,0
       0      .1       0   307.5    .045       0   318.5      .1       0
   330.4     .06       0   430.4      .1       0
Bank Sta=307.5,318.5
XS Rating Curve= 0 ,0
Exp/Cntr(USF)=0,0
Exp/Cntr=0.3,0.1

Type RM Length L Ch R = 1 ,7512    ,501.5,498.1,501.7
XS GIS Cut Line= 6
1645970.90576075382269.2009828391645957.35985608382371.446185172
1645951.23421218  382462.2425915 1645988.9677325382633.126436085
1646006.07990301382706.1548333321646048.15035692382882.482892752
#Sta/Elev= 30
       0   862.6    43.7  832.03      72  813.85   100.2  801.56   112.3  794.55
   116.3  793.29   124.3  792.02   144.3   791.5   208.8  791.66   298.9  790.39
   315.3  788.45   323.5  788.17     332 788.431   339.9  790.41   352.2  791.65
   364.4   799.7   397.9  801.87   401.4  803.42   409.6  809.11   444.1   826.1
   475.4  836.09   495.9  840.93   537.1   856.8   545.3  861.47   565.8  875.91
   578.2  881.92   590.9  886.42   598.7  890.76   615.2  902.44   625.4  911.58
#Mann= 4 ,-1,0
       0      .1       0   315.3    .045       0     332     .06       0
  429.14      .1       0
Bank Sta=315.3,332
XS Rating Curve= 0 ,0
Exp/Cntr(USF)=0,0
Exp/Cntr=0.3,0.1

Type RM Length L Ch R = 1 ,7014    ,506.4,510.7,509.7
XS GIS Cut Line= 6
1645405.84586726382343.3484723421645529.34430793382478.072284251
1645627.29194668382623.2731093321645668.68031535382697.724732086
1645704.11692426382793.9085948321645733.95610343382895.870005086
#Sta/Elev= 30
       0  932.26    18.3  925.49    30.7  918.69    64.7  892.02      93  881.08
   120.2  866.69   135.5  854.38     144  850.82   150.6  850.05   166.7  838.21
   201.8  819.23   229.5  808.96   244.3  797.51   253.7  788.53   264.3  784.22
   299.7782.5314   306.6  781.83   308.9782.5121   316.2  785.75     396  783.43
   428.1  785.68   463.2  784.85   484.5  788.95     501  796.77   539.9  806.77
   569.2   818.8   602.6  847.81   623.4  863.76   640.1  879.02   651.9  886.63
#Mann= 5 ,-1,0
       0      .1       0   299.7    .045       0   308.9      .1       0
  437.96     .06       0  543.15      .1       0
Bank Sta=299.7,308.9
XS Rating Curve= 0 ,0
Exp/Cntr(USF)=0,0
Exp/Cntr=0.3,0.1

Type RM Length L Ch R = 1 ,6504    ,501.3,500.2,499.2
XS GIS Cut Line= 6
1645062.14183025382486.1447746751645129.78834851382654.297981679
 1645195.1031785382816.6523157511645221.40102617382886.914314345
1645240.39573884382973.5827761741645256.53284568383067.912311926
#Sta/Elev= 30
       0  958.46    24.9  941.06    45.7  928.69    67.3   918.7    80.2  907.58
   101.7  891.22     166  849.94   198.2  825.07   215.5  814.12   221.7  811.12
   241.1   805.5   265.6  795.32   291.5  775.32   295.8  774.93   306.3775.3324
     320  778.69   347.5   777.4   364.7  780.62   409.8  780.94   441.6  783.21
   461.6  787.11   475.2  792.57   490.3  793.42   498.7  797.82   518.9   805.5
   539.2  806.08   559.5  815.35   575.8  819.48   587.9   825.2   615.7  829.82
#Mann= 5 ,-1,0
       0      .1       0   291.5    .045       0   306.3      .1       0
  326.25     .06       0  431.27      .1       0
Bank Sta=291.5,306.3
XS Rating Curve= 0 ,0
Exp/Cntr(USF)=0,0
Exp/Cntr=0.3,0.1