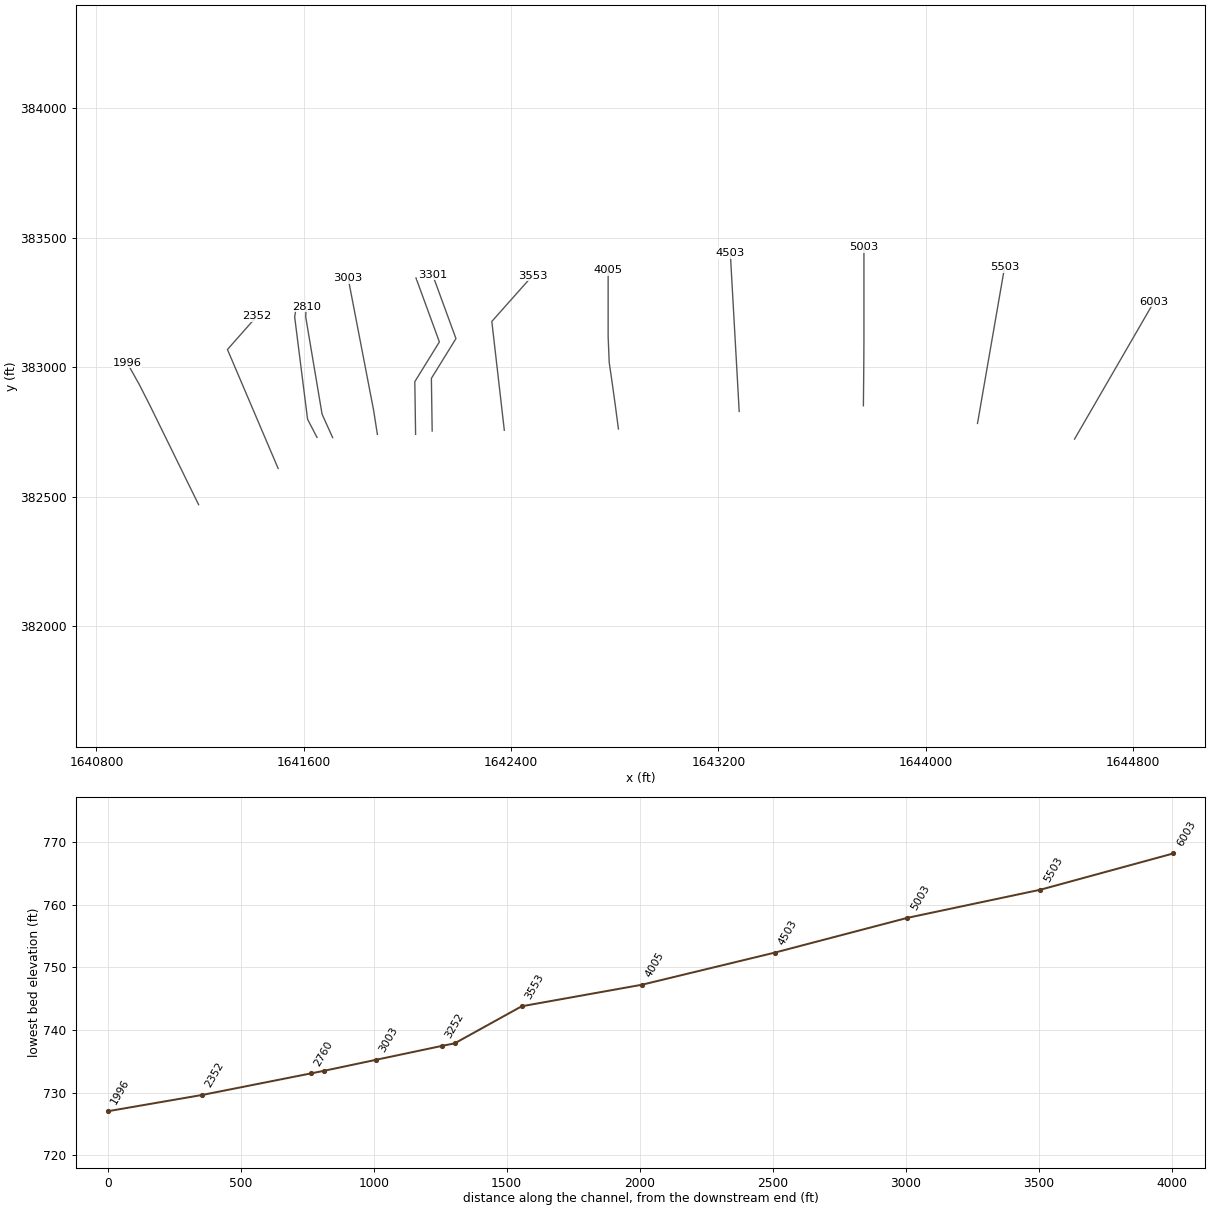
HEC-RAS study UPPERRN.prj: UPPERRN

--- UPPERRN.g01 (geometry) --- (continued)

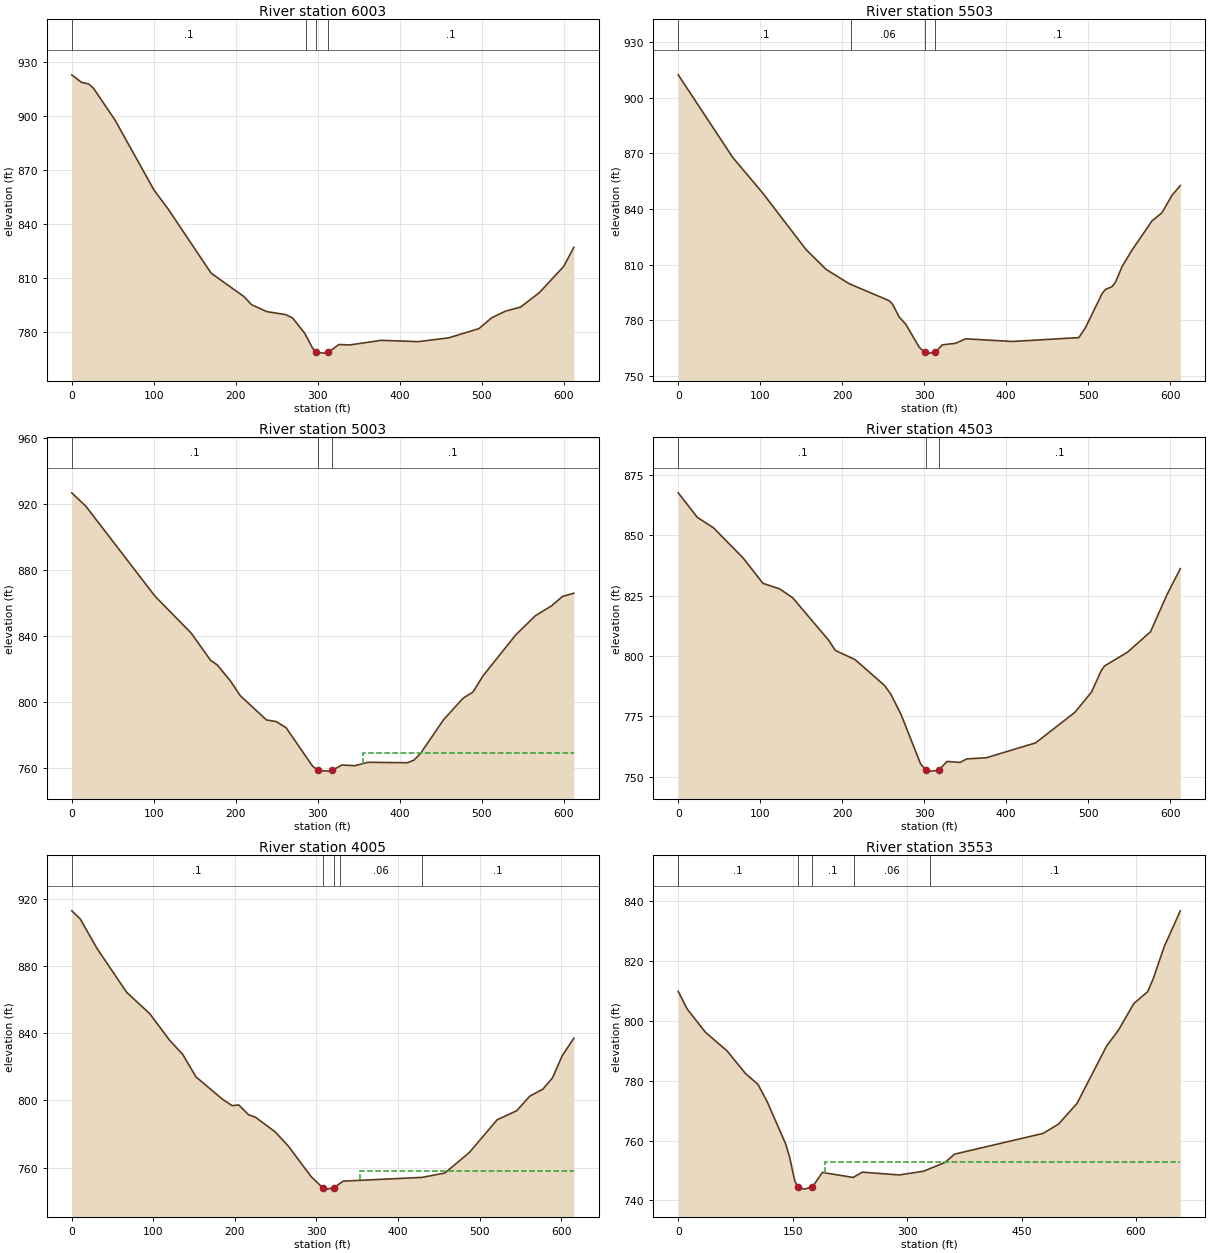
Type RM Length L Ch R = 1 ,6003    ,496.7,500,502.1
XS GIS Cut Line= 6
1644573.84425043382722.6551284191644620.81659742382803.789152503
1644664.65870135382879.513082415  1644702.236054382944.420104846
1644833.75908493383171.5938630851644880.73044768383252.728215262
#Sta/Elev= 30
       0  922.76    11.8  918.62    20.7  917.66    26.5  915.32    52.8  897.62
   100.3  858.77   117.7  848.14   169.9  812.66   210.2  799.52   219.4  795.06
   237.9  791.24     261  789.55   269.4  787.71   284.1  779.26   293.4  771.23
     298  768.63   307.2  768.17     313 768.624   325.7  772.92   339.6  772.74
   377.7  775.28   422.8  774.55   459.8  776.66   496.7  781.78   512.4  787.84
   529.1  791.49   547.6  793.77   570.7  801.88   600.2  816.39   612.5  826.96
#Mann= 4 ,-1,0
       0      .1       0  286.25     .06       0     298    .045       0
     313      .1       0
Bank Sta=298,313
XS Rating Curve= 0 ,0
Exp/Cntr(USF)=0,0
Exp/Cntr=0.3,0.1

Type RM Length L Ch R = 1 ,5503    ,498.7,500,501.5
XS GIS Cut Line= 6
1644199.44900183382783.0319761781644215.46012467382875.404494837
1644243.21236576383035.5173635931644260.29107176383134.048006415
1644288.04396901383294.1605470931644304.05509184383386.533065751
#Sta/Elev= 30
       0  912.34    66.5  867.82     103  848.69   155.8  818.24   180.2  807.57
   208.6  799.77   257.3  790.64   261.3  788.85   269.5  781.86   277.6  777.93
   293.8  765.68   300.5 762.782   306.4  762.38   313.3  762.76   322.2  766.86
   338.5  767.69   350.7  770.09   407.5  768.66   488.7  770.74   496.8   776.1
   517.1  794.47   521.2   796.7   529.3  798.23   533.3  800.49   541.5  809.04
   553.6  817.91     578  833.66   590.1     838   602.4  847.45   612.5  852.66
#Mann= 4 ,-1,0
       0      .1       0  211.25     .06       0   300.5    .045       0
   313.3      .1       0
Bank Sta=300.5,313.3
XS Rating Curve= 0 ,0
Exp/Cntr(USF)=0,0
Exp/Cntr=0.3,0.1

Type RM Length L Ch R = 1 ,5003    ,499.6,500,500.6
XS GIS Cut Line= 5
1643759.22448859382851.0502128451643760.16641584382944.800353423
1643760.92691301383032.300178424   1643761.32455383107.300356507
   1643761.32455383463.550300166
#Sta/Elev= 30
       0  926.52    17.5  918.22   101.5  863.91   145.5  841.63   169.5  824.97
   177.5  822.23   193.5  812.58   205.5  803.63   237.5  788.91   249.5  787.88
   261.5  784.18   293.5  761.09   300.4758.2943   313.5  757.89   317.5  758.29
   329.5  761.59   345.5   761.2   361.5  763.24   409.5  762.98   417.5  764.56
   425.5  768.63   453.5     789   477.5  802.12   489.5  805.84   501.5   815.5
   541.5  840.37   565.5  852.02   585.5  858.11   598.7  863.77   612.5  865.69
#Mann= 3 ,-1,0
       0      .1       0   300.4    .045       0   317.5      .1       0
#XS Ineff= 2 , 0
                          355.28           768.7
Permanent Ineff=
       F       F
Bank Sta=300.4,317.5
XS Rating Curve= 0 ,0
Exp/Cntr(USF)=0,0
Exp/Cntr=0.3,0.1

Type RM Length L Ch R = 1 ,4503    ,497.5,497.9,496.3
XS GIS Cut Line= 6
1643279.99742867382829.2621986721643274.83372509382922.858140096
  1643269.912147383010.2198420021643255.84951109383259.823673502
1643250.92793301383347.1853754221643245.76324518383440.804610759
#Sta/Elev= 30
       0  867.56    23.3  857.42    43.3  852.99    79.4  840.49   103.4  830.07
   123.5  827.83   139.5  824.16   183.6   806.5   191.6  802.32   215.6  798.54
   251.7   787.8   259.7  783.98   271.7  775.87   295.7  755.32   302.7  752.63
   307.8  752.33   317.6 752.609   327.8  756.34   343.8  755.93   351.8  757.38
   375.9  757.87     436  764.03     484  776.71   504.1  785.03   516.1  793.98
   520.1  795.88   548.1  801.58   576.2  810.05   596.2  825.38   612.5  836.16
#Mann= 3 ,-1,0
       0      .1       0   302.7    .045       0   317.6      .1       0
Bank Sta=302.7,317.6
XS Rating Curve= 0 ,0
Exp/Cntr(USF)=0,0
Exp/Cntr=0.3,0.1

Type RM Length L Ch R = 1 ,4005    ,454.8,452.5,454.2
XS GIS Cut Line= 6
1642814.08792743382761.6822813451642801.60370043382855.834324002
1642789.40260933382943.5992403331642778.50007209383018.416347921
 1642774.3839386383118.416476011 1642774.3839386383374.666291595
#Sta/Elev= 30
       0   912.7    10.3  907.95    31.1  890.21    67.4  864.19    95.7  851.49
   119.9   835.8   136.1  827.28   152.2  814.01   184.5  800.77   196.7  796.83
   204.7   797.3   216.9  791.39     225  790.04   249.2  781.34   265.3  772.94
   293.3  754.74   307.4748.1389   313.2  747.22   321.4  748.13   332.7  751.97
   429.4   754.2   457.4  756.79   487.7  769.14   521.4  788.44   545.4  793.82
   561.4  802.46   577.4  806.62   589.4   813.4   601.4  826.72   615.5  836.94
#Mann= 5 ,-1,0
       0      .1       0   307.4    .045       0   321.4      .1       0
  329.19     .06       0  429.28      .1       0
#XS Ineff= 2 , 0
                          353.27          757.84
Permanent Ineff=
       F       F
Bank Sta=307.4,321.4
XS Rating Curve= 0 ,0
Exp/Cntr(USF)=0,0
Exp/Cntr=0.3,0.1

Type RM Length L Ch R = 1 ,3553    ,259.1,252.3,247.9
XS GIS Cut Line= 3
1642373.76568515 382756.836233551642325.62112678383176.596601813
1642482.09094148383352.625143343
#Sta/Elev= 30
       0  809.78    11.8  803.86    35.9  796.05    64.1  789.89    88.3  782.31
   104.4  778.76   116.5  773.01   140.6  758.98   145.7  754.73   152.7  746.56
   156.7  744.43   164.8  743.78   175.7744.4239   188.9  749.35   229.2  747.68
   241.3  749.45   289.6  748.51   321.8  749.77     350  752.75   362.1  755.46
   478.1  762.37   498.5   765.5   522.6  772.37   561.6  791.63   576.8  796.78
   597.1  805.72   615.1  809.63   622.6  814.02   636.7  824.57     658  836.65
#Mann= 5 ,-1,0
       0      .1       0   156.7    .045       0   175.7      .1       0
     230     .06       0     330      .1       0
#XS Ineff= 2 , 0
                          192.74          752.72
Permanent Ineff=
       F       F
Bank Sta=156.7,175.7
XS Rating Curve= 0 ,0
Exp/Cntr(USF)=0,0
Exp/Cntr=0.3,0.1

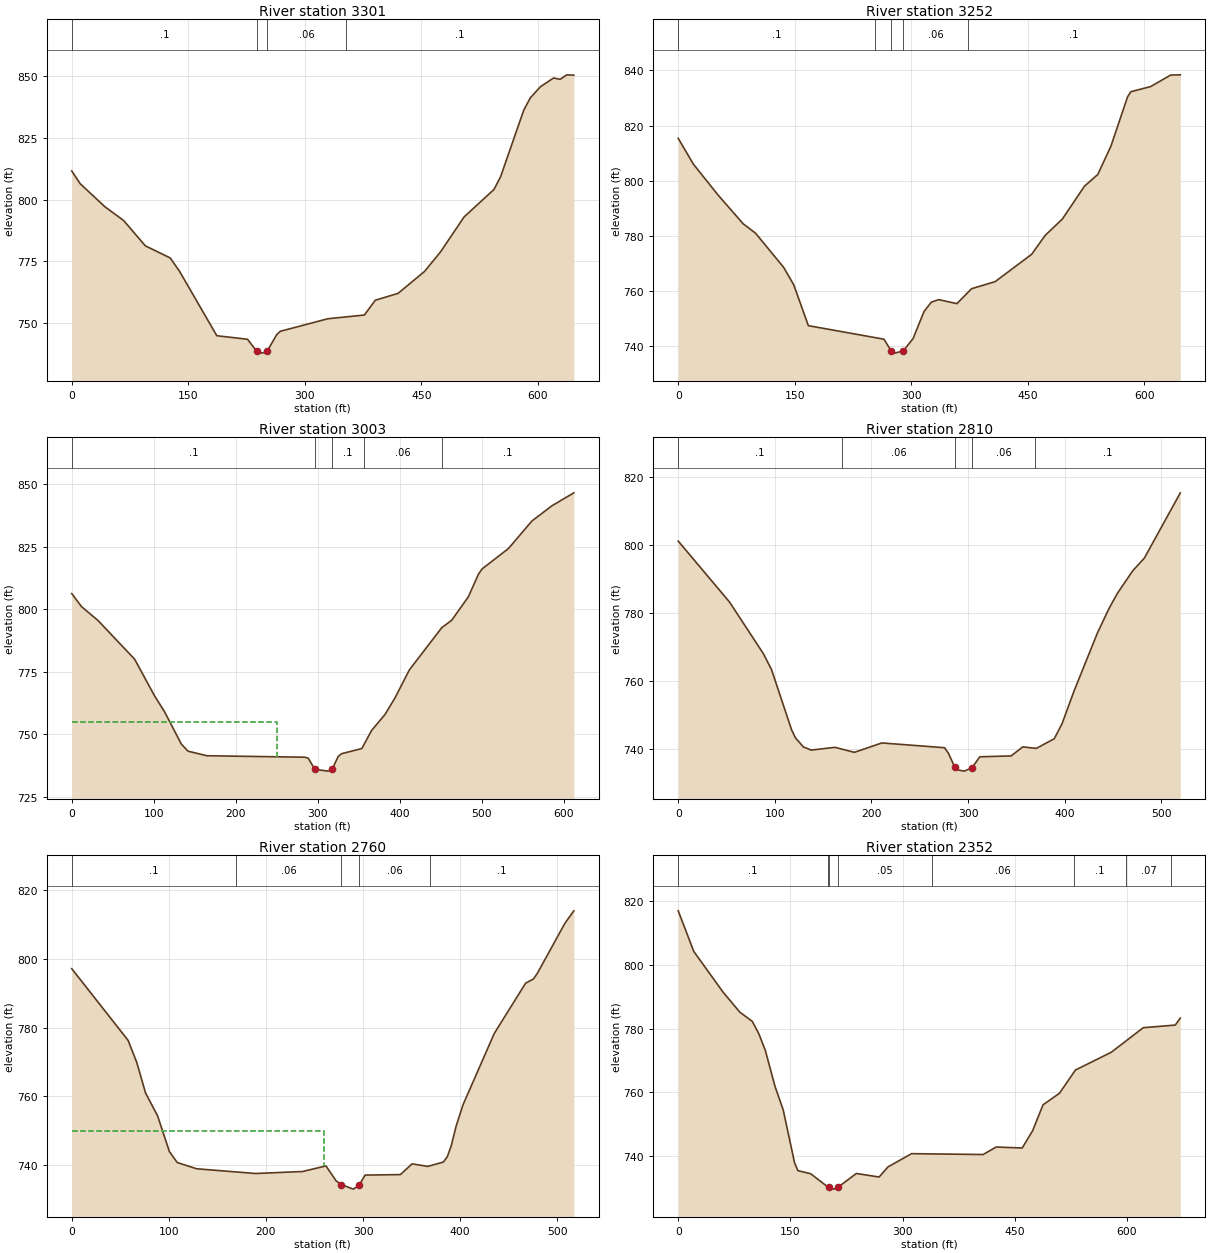
Type RM Length L Ch R = 1 ,3301    ,48.5,48.4,48.1
XS GIS Cut Line= 4
1642095.42995709382753.8271986521642092.42092219382956.937054263
1642187.20552148383110.3978340591642096.93447454 383357.13869569
#Sta/Elev= 30
       0  811.56    10.7  806.46    42.7  797.08    66.7  791.54    94.7  781.27
   126.7  776.38   138.7  770.98   186.7   744.9   226.2  743.47   238.2 738.565
     245  737.86   251.3738.5465   263.8  745.36   268.5  746.71   329.6  751.77
   376.6  753.28   390.7  759.27   419.9  762.03   453.9  770.87   474.9  778.95
     505  792.99   543.4  804.07   551.9   809.2   581.7  836.16   590.2  841.15
     603   845.6     620  849.18   628.6  848.66   637.1  850.47   646.2  850.33
#Mann= 4 ,-1,0
       0      .1       0   238.2    .045       0   251.3     .06       0
  353.13      .1       0
Bank Sta=238.2,251.3
XS Rating Curve= 0 ,0
Exp/Cntr(USF)=0,0
Exp/Cntr=0.3,0.1

Type RM Length L Ch R = 1 ,3252    ,243.1,248.9,256.2
XS GIS Cut Line= 4
1642031.48796551382741.0388003361642028.47893061382944.148655947
 1642123.2635299383097.6094357421642032.99248296383344.350297374
#Sta/Elev= 30
       0  815.36    19.5     806    51.5  794.72    83.5  784.38    99.5  780.95
   135.5  768.63   148.7  762.21   167.5  747.41   264.7  742.51   274.1  738.28
   278.7  737.45   289.6  738.27   302.3  742.75   316.4  752.57   325.8  755.95
   335.2  756.85   358.7   755.4   377.5  760.81   407.9  763.38   454.8  773.27
   472.4   780.2   494.3  786.05   522.9  798.02     540  802.25     557   812.6
   578.3  830.39   582.5  832.26   608.1  834.14   633.7   838.3   646.2  838.39
#Mann= 5 ,-1,0
       0      .1       0  253.13     .06       0   274.1    .045       0
   289.6     .06       0  373.13      .1       0
Bank Sta=274.1,289.6
XS Rating Curve= 0 ,0
Exp/Cntr(USF)=0,0
Exp/Cntr=0.3,0.1

Type RM Length L Ch R = 1 ,3003    ,194,193.8,193.6
XS GIS Cut Line= 6
1641884.05271401382740.7220214161641869.56225742382833.404578835
1641838.80313259382992.9669237581641819.87436467383091.158984587
1641805.67754267383164.8031942551641771.36921234383342.776263505
#Sta/Elev= 30
       0  806.21      12  800.98    32.2   795.4    76.7  779.98   101.1  765.28
   113.3  758.92   133.7  746.04   141.8   743.2   164.9  741.37   284.4  740.78
   288.5   740.4   296.6  735.91   312.9  735.22   317.6  735.93   325.1   741.1
   329.2  742.19   353.9  744.25   365.9  751.52   382.2  757.87   394.4  764.52
   411.9  775.69   451.4  792.57   463.6  795.57     484  804.99   496.2  813.98
   500.7  816.09   532.9  824.26   561.4  835.23   585.8  841.32   612.6  846.51
#Mann= 5 ,-1,0
       0      .1       0   296.6    .045       0   317.6      .1       0
  356.31     .06       0  451.31      .1       0
#XS Ineff= 2 , 0
             250     755
Permanent Ineff=
       F       F
Bank Sta=296.6,317.6
XS Rating Curve= 0 ,0
Exp/Cntr(USF)=0,0
Exp/Cntr=0.3,0.1

Type RM Length L Ch R = 1 ,2810    ,50.3,50,49.6
XS GIS Cut Line= 4
1641711.51586168382728.1829398291641670.64934617382818.799995943
 1641607.5727679383193.7058555531641609.34957292383233.683968544
#Sta/Elev= 30
       0  801.08      53   783.2    88.1     768    96.6  763.28   117.4  745.55
   121.4  743.22   129.6  740.58   137.7  739.66   162.1  740.48   182.3     739
   210.7  741.76   275.6  740.36   279.6  738.74   286.4734.5517   287.8  733.92
   295.9  733.48     304  734.44   312.1  737.69   344.5  737.95   356.6  740.61
   370.5  740.15   389.2  743.01   397.3  747.47   409.4  756.85   433.8  774.06
   445.9  781.31   454.4  785.69   470.3  792.34   482.4  796.08   519.6  815.26
#Mann= 5 ,-1,0
       0      .1       0  169.41     .06       0   286.4    .045       0
     304     .06       0  369.41      .1       0
Bank Sta=286.4,304
XS Rating Curve= 0 ,0
Exp/Cntr(USF)=0,0
Exp/Cntr=0.3,0.1

Type RM Length L Ch R = 1 ,2760    ,400.1,407.7,409.3
XS GIS Cut Line= 4
1641651.10449093 382729.071342341641614.67998799382799.255140703
1641564.92944738383193.7058555531641571.14826495383233.683968544
#Sta/Elev= 30
       0  797.09      58  776.28      67  769.83      76  760.99    88.4  754.35
   100.5  744.01   108.6  740.79   128.7  738.97   189.2   737.6   237.6  738.17
   261.8   739.8   272.3  735.45   277.7734.3705     290  733.06   295.9734.1996
   302.1  737.14   338.4  737.28   350.5   740.4   366.6  739.66   382.7  740.92
   386.8   742.5   390.8  745.63   395.9  751.39   402.9  757.53   435.2  778.31
   467.4  792.87   475.5  794.12   479.5  795.74   507.9  810.29   517.1   813.9
#Mann= 5 ,-1,0
       0      .1       0  169.07     .06       0   277.7    .045       0
   295.9     .06       0  369.07      .1       0
#XS Ineff= 2 , 0
             260     750
Permanent Ineff=
       F       F
Bank Sta=277.7,295.9
XS Rating Curve= 0 ,0
Exp/Cntr(USF)=0,0
Exp/Cntr=0.3,0.1

Type RM Length L Ch R = 1 ,2352    ,354.9,355.4,355.4
XS GIS Cut Line= 3
1641501.14556475382609.3935235511641305.55829638383068.271345487
 1641419.9016225383197.659846099
#Sta/Elev= 30
       0  816.97    20.8  804.23    59.9  791.47    82.4  785.17    99.1  782.27
   107.8  778.39   116.5  773.17   129.5  761.82   140.4  754.49   155.6  737.91
     160  735.43     177  734.48     201  730.16   207.8  729.63   213.3730.1572
   238.2  734.54   268.7  733.43   280.6  736.62   312.1  740.76   407.8  740.49
   425.2  742.84     460  742.54   473.9  747.91   487.9  756.09   509.9  759.72
   531.2     767   579.2  772.59     622   780.3   664.7  781.11   671.5   783.3
#Mann= 8 ,-1,0
       0      .1       0     200     .05       0     201    .045       0
   213.3     .05       0     340     .06       0  528.82      .1       0
  598.82     .07       0  658.82     .05       0
Bank Sta=201,213.3
XS Rating Curve= 0 ,0
Exp/Cntr(USF)=0,0
Exp/Cntr=0.3,0.1

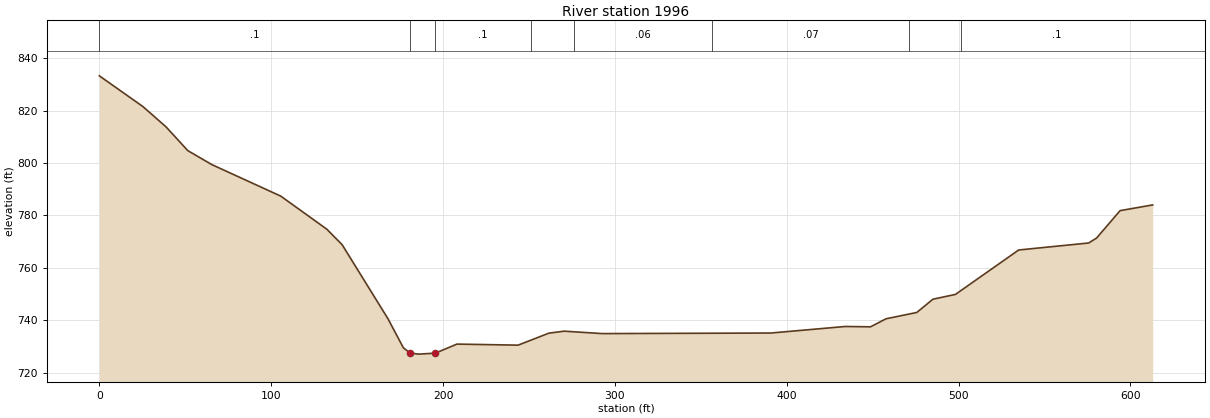
Type RM Length L Ch R = 1 ,1996    ,400.4,400.3,399.9
XS GIS Cut Line= 6
1641194.22425249382469.709999978  1641081.364242382699.768266901
1641037.32200724382789.5472868231641004.28926492382856.881141647
1640964.48028942382934.8160251521640918.54206108383017.053393482
#Sta/Elev= 30
       0  833.34    25.4  821.58    38.8  813.85    51.5  804.76    65.5  799.42
   105.6  787.38   132.4  774.74   141.3  768.82     168  740.51   176.9  729.48
   180.8727.4416   185.8  727.03   195.5   727.4   208.1  730.86   243.7  730.46
   261.6  735.04   270.5   735.8   292.7  734.87   390.8  735.09   434.1  737.59
   448.8  737.46   457.8  740.53   475.7  742.94   485.1  748.01   498.2  749.84
     535  766.81   575.7  769.48   580.3  771.36     594  781.84     613  784.03
#Mann= 8 ,-1,0
       0      .1       0   180.8    .045       0   195.5      .1       0
  251.25     .05       0  276.25     .06       0  356.25     .07       0
  471.25     .06       0  501.25      .1       0
Bank Sta=180.8,195.5
XS Rating Curve= 0 ,0
Exp/Cntr(USF)=0,0
Exp/Cntr=0.3,0.1