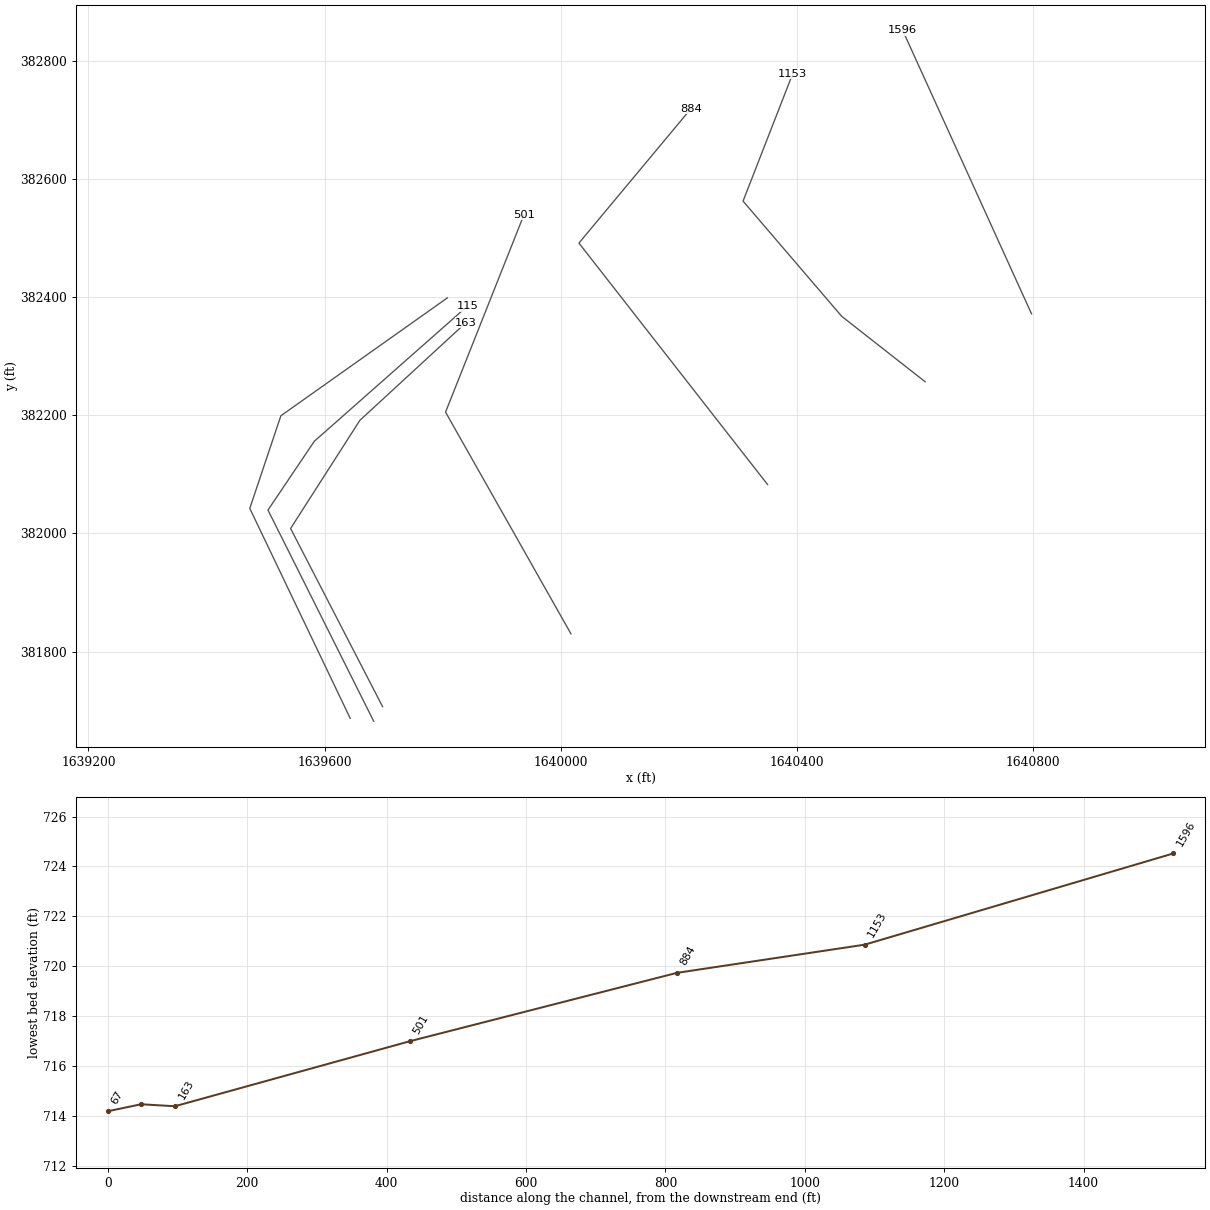
HEC-RAS study UPPERRN.prj: UPPERRN

--- UPPERRN.g01 (geometry) --- (continued)

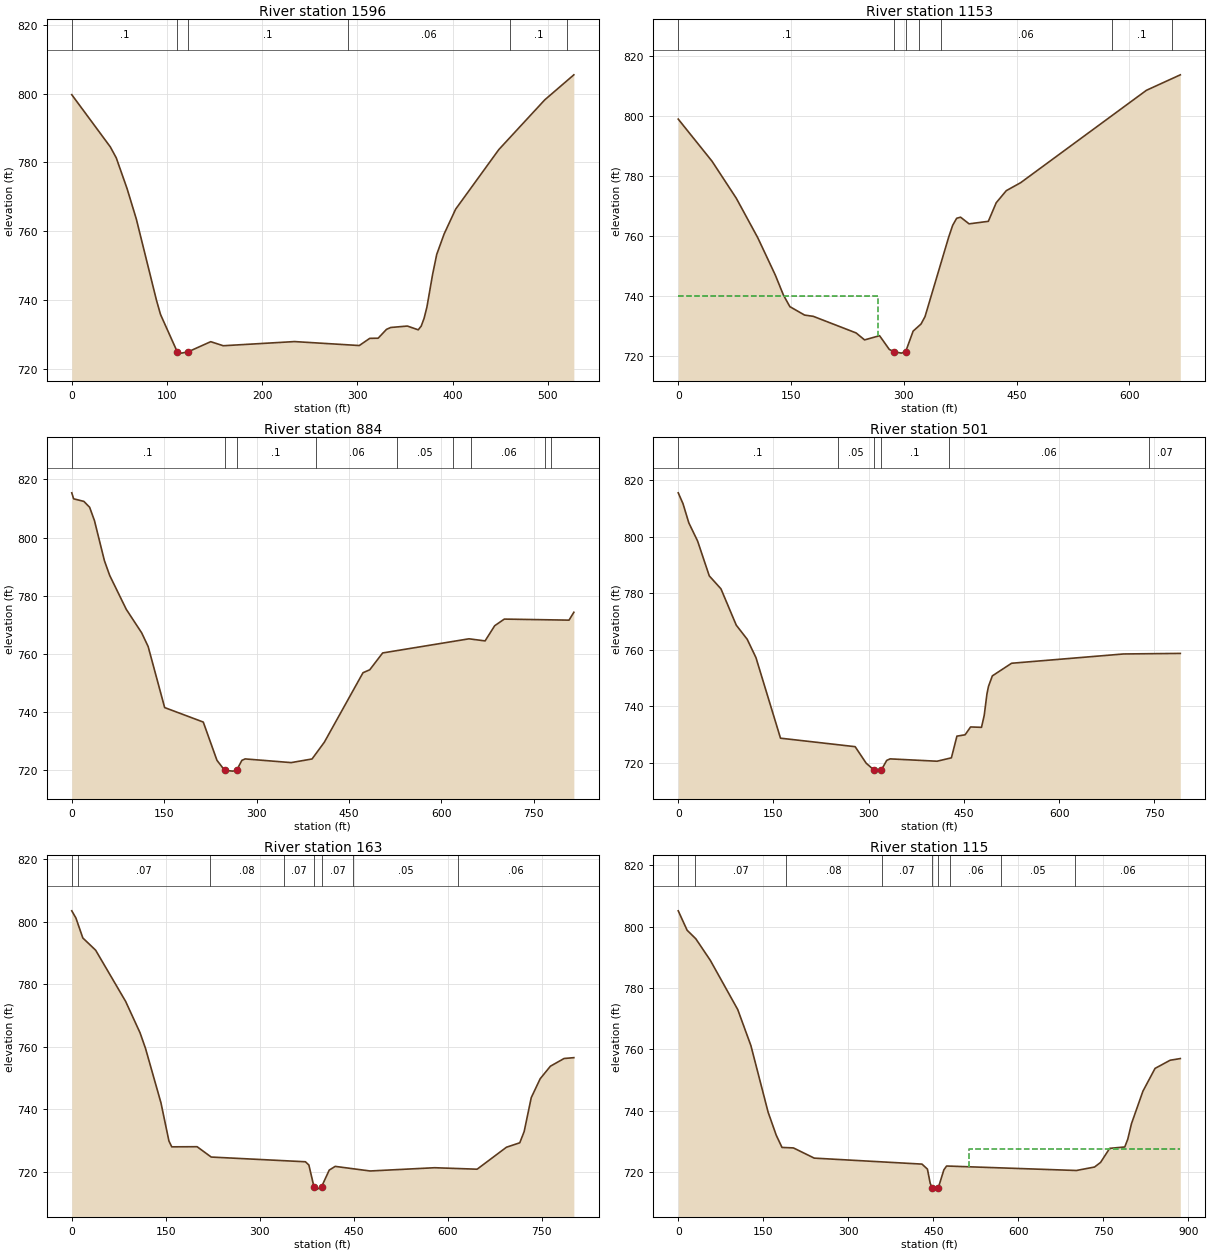
Type RM Length L Ch R = 1 ,1596    ,444,443,449.3
XS GIS Cut Line= 2
1640797.03139863382371.6797666131640578.87636853382851.620832835
#Sta/Elev= 30
       0  799.72    40.5  784.52    46.7  781.35    58.1  772.37    67.8  763.52
    88.9  739.96    93.2  735.76   110.8  724.88   115.2  724.52     122  724.88
   145.9  727.85   159.1  726.67   233.9  727.88   301.9  726.73   312.9  728.82
   321.7  728.86   330.5  731.44   334.9  731.98   352.4   732.4   363.8   731.3
   366.9  732.37   369.9   734.6   372.9  737.89   378.9  747.44   383.2  753.23
     391   759.2   403.1  766.42   448.4  783.74   496.7  798.23   527.2   805.5
#Mann= 6 ,-1,0
       0      .1       0   110.8    .045       0     122      .1       0
     290     .06       0     460      .1       0     520     .07       0
Bank Sta=110.8,122
XS Rating Curve= 0 ,0
Exp/Cntr(USF)=0,0
Exp/Cntr=0.3,0.1

Type RM Length L Ch R = 1 ,1153    ,269.6,269.4,268.8
XS GIS Cut Line= 4
1640616.83534376382256.7797690351640475.47088426382367.677750199
1640308.51458295382562.6632115861640392.60206317382778.365878245
#Sta/Elev= 30
       0  798.86      45  784.81    77.2   772.5   105.8  759.33   129.2  746.84
   139.9  740.24   148.5  736.35   168.1  733.54   179.7  733.12   236.6  727.59
   247.9  725.27   267.8  726.67   280.9  722.06   287.6  721.32   296.7  720.86
   302.5721.3322   312.5   728.2     323  730.57   328.3  733.03   359.8  759.55
   365.1  763.47   370.4  765.81   375.6  766.17   386.9  763.95   412.5  764.79
     423  770.98   436.4  775.01   455.6  777.68   622.8  808.46   667.9  813.62
#Mann= 7 ,-1,0
       0      .1       0   287.6    .045       0   302.5      .1       0
  319.67     .07       0  349.67     .06       0  576.37      .1       0
  656.37     .06       0
#XS Ineff= 2 , 0
             266     740
Permanent Ineff=
       F       F
Bank Sta=287.6,302.5
XS Rating Curve= 0 ,0
Exp/Cntr(USF)=0,0
Exp/Cntr=0.3,0.1

Type RM Length L Ch R = 1 ,884     ,384.1,383,380.8
XS GIS Cut Line= 6
1640349.99118665382082.7931582551640192.23231581382284.724512912
1640130.66813449382363.526848755 1640084.4946704382422.628764666
1640030.62601173 382491.581054591640220.31912778382719.253648512
#Sta/Elev= 30
       0  815.41       3  813.36    19.7  812.46      29  810.44    36.8  805.89
      53  792.09    61.5  787.04    88.5  775.35   113.5  767.27     124  762.57
   150.8  741.58   213.5   736.6   235.7  723.45   248.2720.0032   261.1  719.73
   267.6  719.98   276.1  723.42   281.4  723.93   356.2  722.66   390.1  723.91
   410.1   729.7   472.8  753.56   483.8  754.58   504.7  760.36   644.9  765.22
     671   764.5   686.6  769.72   702.2     772   807.3  771.64   815.1  774.34
#Mann= 9 ,-1,0
       0      .1       0   248.2    .045       0   267.6      .1       0
  396.25     .06       0  528.75     .05       0  618.75     .07       0
  648.75     .06       0  768.75     .05       0  778.75     .06       0
Bank Sta=248.2,267.6
XS Rating Curve= 0 ,0
Exp/Cntr(USF)=0,0
Exp/Cntr=0.3,0.1

Type RM Length L Ch R = 1 ,501     ,341.8,337.5,328.6
XS GIS Cut Line= 6
1640017.10434817381829.9771237521639970.94466358381911.575713843
1639927.86207259381987.7343541681639841.69721867382140.051962927
1639804.76979908382205.3310318441639937.51956006382539.583927818
#Sta/Elev= 30
       0  815.57     7.5  811.74    16.7  804.92    30.5   798.5    48.9  786.15
    67.3  781.56    91.4   768.7   108.6  763.71   122.4  757.22   161.1  728.66
   278.7  725.65   296.1  719.79   308.2717.4068   315.4  716.99     320  717.41
   328.4  720.79   333.8  721.33   407.7   720.5   430.3   721.7     439  729.38
   451.9  729.86   460.5  732.64   477.7   732.5     482  736.72   486.3  744.33
   488.7  746.98   494.8  750.73   525.1   755.2   701.5  758.49   790.9  758.69
#Mann= 6 ,-1,0
       0      .1       0  251.25     .05       0   308.2    .045       0
     320      .1       0  426.25     .06       0  741.25     .07       0
Bank Sta=308.2,320
XS Rating Curve= 0 ,0
Exp/Cntr(USF)=0,0
Exp/Cntr=0.3,0.1

Type RM Length L Ch R = 1 ,163     ,48.4,48.4,48.1
XS GIS Cut Line= 4
1639698.10574667381706.7094713231639542.36110895382008.327607747
1639659.71798385382191.4920760491639839.59207248382357.107852776
#Sta/Elev= 30
       0  803.48     6.6  801.19    17.7  794.78    38.1  790.88      86  774.48
     109  764.43   117.7  759.45   142.4     742   155.1   729.8   159.6  727.92
   200.1  727.96   222.6  724.65     373  723.14   378.5   722.1   386.6715.1614
     392  714.38   398.8  715.15     411  720.47   420.5  721.66   476.2  720.19
   579.3  721.23   647.1  720.76   693.9  727.79   715.2  729.22   722.2  732.82
   733.5  743.67   747.8  749.73   764.1  753.74   785.9   756.2   801.5  756.47
#Mann= 8 ,-1,0
       0      .1       0      10     .07       0     220     .08       0
  339.46     .07       0   386.6    .045       0   398.8     .07       0
  449.46     .05       0  616.99     .06       0
Bank Sta=386.6,398.8
XS Rating Curve= 0 ,0
Exp/Cntr(USF)=0,0
Exp/Cntr=0.3,0.1

Type RM Length L Ch R = 1 ,115     ,44.1,47.7,48.9
XS GIS Cut Line= 4
1639683.12921453381681.9162822991639504.08110654382039.511494055
1639582.50859221382155.9611446051639841.55490191382384.676382715
#Sta/Elev= 30
       0  805.11    15.7  798.78      31  796.01    56.6  788.99     105  772.95
   128.2  761.22   158.6  739.53   172.9  732.03   183.1  728.04   203.3  727.88
     240  724.56   430.1  722.61   439.7  720.98   444.6  716.36   447.9  714.96
   450.1  714.46     459  714.95   468.7  720.74   473.5  721.99   702.5  720.53
   734.6  721.66   745.2  723.16   761.2  727.74   787.9  728.19   793.2  730.73
   799.7  735.76   819.9  746.35   841.3  753.78   867.9  756.44   885.9  756.99
#Mann= 9 ,-1,0
       0      .1       0      30     .07       0     190     .08       0
     360     .07       0   447.9    .045       0     459     .07       0
  479.92     .06       0  570.31     .05       0  700.31     .06       0
#XS Ineff= 2 , 0
                          512.58          727.69
Permanent Ineff=
       F       F
Bank Sta=447.9,459
XS Rating Curve= 0 ,0
Exp/Cntr(USF)=0,0
Exp/Cntr=0.3,0.1

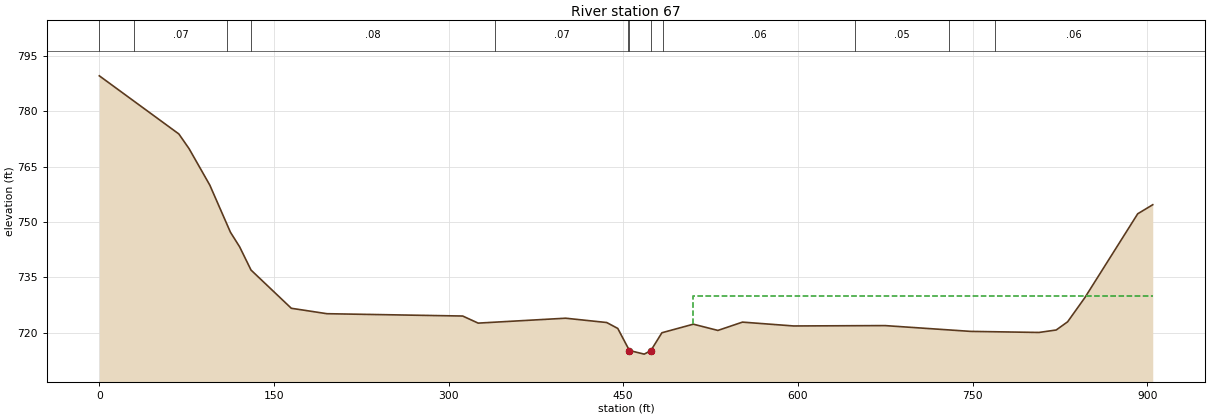
Type RM Length L Ch R = 1 ,67      ,,,
XS GIS Cut Line= 4
 1639643.2660855381686.9671933021639473.26313588382042.328197671
 1639525.9092106382199.169628612  1639807.785069382398.785995264
#Sta/Elev= 30
       0  789.57    68.3  773.82    77.1  769.83    94.9  759.96   112.6  747.21
   120.5  743.25   130.3  736.95   164.9   726.6   195.5  725.13   312.1   724.5
   325.4  722.58   400.5  723.91   435.8  722.74   445.3  721.14   455.3  715.16
     468  714.18   473.7  715.12   483.2  719.97   510.2  722.29   531.3   720.6
   552.4  722.85   596.3  721.81   674.8  721.91   748.3  720.34   807.1  720.05
   821.9  720.72   831.7  722.94   846.4  729.44   891.9   752.2   904.8  754.65
#Mann= 12 ,-1,0
       0      .1       0      30     .07       0     110      .1       0
     130     .08       0     340     .07       0  453.93      .1       0
   455.3    .045       0   473.7      .1       0  483.93     .06       0
  649.37     .05       0  729.37      .1       0  769.37     .06       0
#XS Ineff= 2 , 0
                             510             730
Permanent Ineff=
       F       F
Bank Sta=455.3,473.7
XS Rating Curve= 0 ,0
Exp/Cntr(USF)=0,0
Exp/Cntr=0.3,0.1
LCMann Table=0

Chan Stop Cuts=-1
Use User Specified Reach Order=0
Composite Channel Slope=5